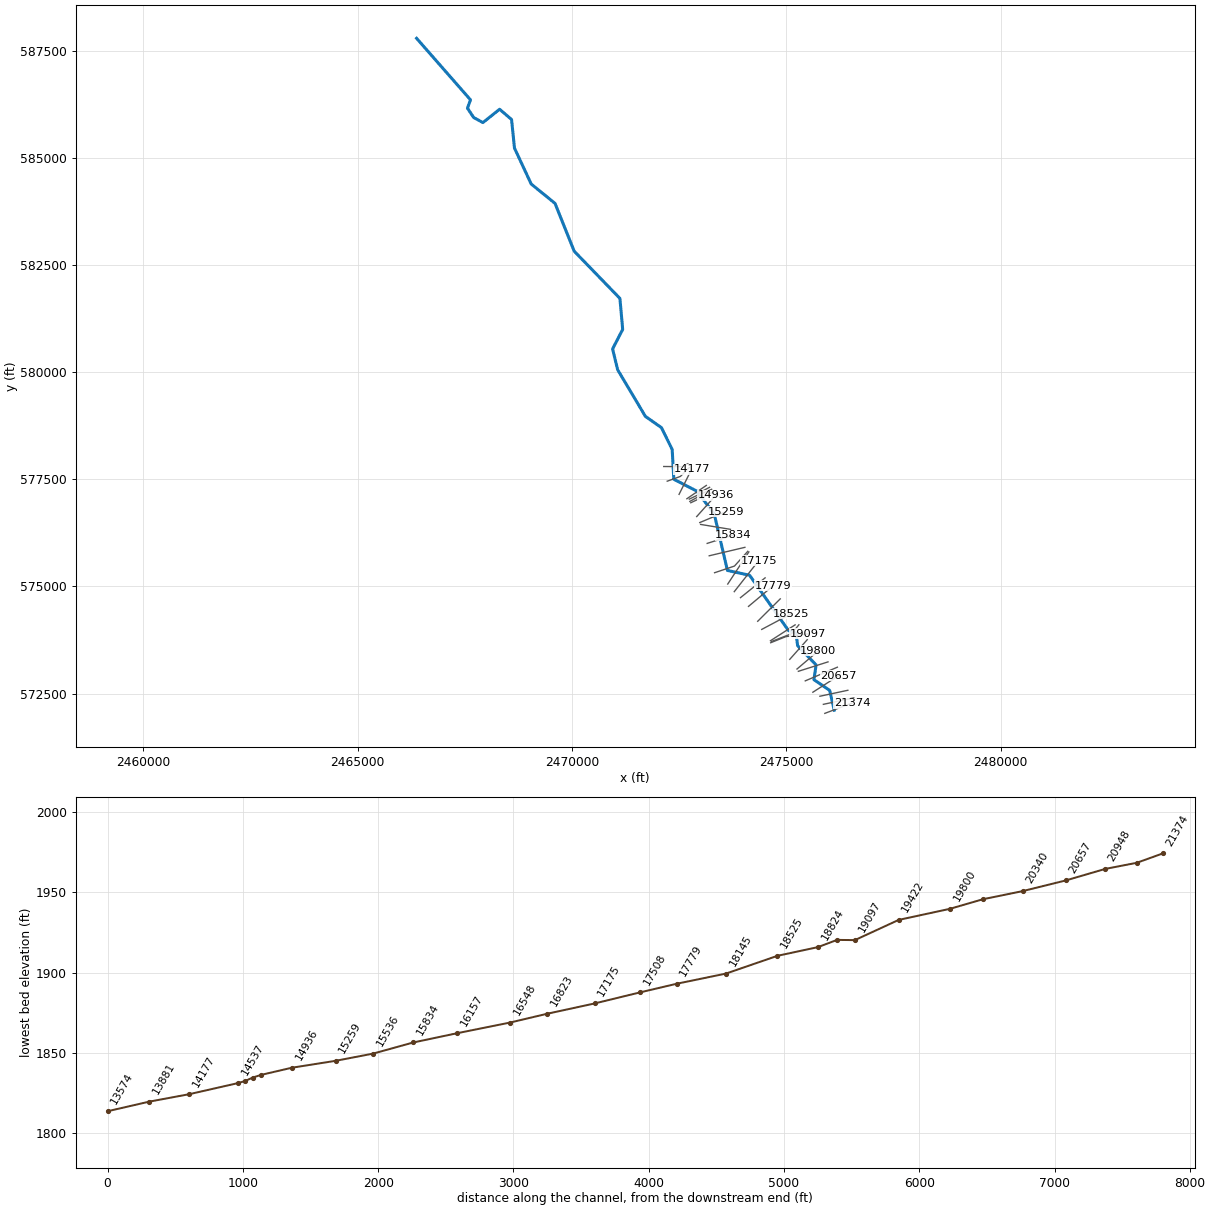
--- MILLERRN.prj (project) ---

Proj Title=MILLERRN
Current Plan=p01
Default Exp/Contr=0,0
English Units
Geom File=g01
Flow File=f01
Plan File=p01
BEGIN DESCRIPTION:
Stream Name: Miller Run
Flood Zone: Approximate
Pendleton County, West Virginia
HEC-RAS Version: 5.0.7
Hydrology Method:
Regression equation
END DESCRIPTION:
DSS Export Rating Curves= 0
DSS Export Rating Curve Sorted= 0
DSS Export Volume Flow Curves= 0
DXF OffsetX= 0
DXF OffsetY= 0
DXF ScaleX= 0
DXF ScaleY= 0

--- MILLERRN.p01 (plan) ---

Plan Title=Floodplain
Program Version=5.07
Short Identifier=Floodplain
Geom File=g01
Flow File=f01
Subcritical Flow
K Sum by GR= 0
Std Step Tol= 0.01
Critical Tol= 0.01
Num of Std Step Trials= 20
Max Error Tol= 0.3
Flow Tol Ratio= 0.001
Split Flow NTrial= 30
Split Flow Tol= 0.02
Split Flow Ratio= 0.02
Log Output Level= 0
Friction Slope Method= 1
Unsteady Friction Slope Method= 2
Unsteady Bridges Friction Slope Method= 1
Parabolic Critical Depth
Global Vel Dist= 0 , 0 , 0
Global Log Level= 0
CheckData=True
Encroach Param=-1 ,0,0, 0
Mapping Interval=1HOUR
Computation Time Step Use Courant=        0
Computation Time Step Use Time Series=    0
Computation Time Step Count To Double=0
Computation Time Step Max Doubling=0
Computation Time Step Max Halving=0
Computation Time Step Residence Courant=0
Run HTab= 0
Run UNet= 0
Run Sediment= 0
Run PostProcess= 0
Run WQNet= 0
Run RASMapper= 0
UNET Theta= 0
UNET Theta Warmup= 0
UNET ZTol= 0
UNET ZSATol= 0
UNET MxIter= 0
UNET Max Iter WO Improvement= 0
UNET MaxInSteps= 0
UNET DtIC= 0
UNET DtMin= 0
UNET MaxCRTS= 0
UNET WFStab= 0
UNET SFStab= 0
UNET WFX= 1
UNET SFX= 1
UNET 1D Methodology=Finite Difference
UNET DSS MLevel= 1
UNET Pardiso=0
UNET DZMax Abort= 0
UNET Use Existing IB Tables= 0
UNET Froude Reduction=False
UNET Froude Limit= 0
UNET Froude Power= 0
UNET D1 Cores= 0
UNET D2 Coriolis=0
UNET D2 Cores= 0
UNET D2 Theta= 1
UNET D2 Theta Warmup= 1
UNET D2 Z Tol= 0.01
UNET D2 Volume Tol= 0.01
UNET D2 Max Iterations= 20
UNET D2 Equation= 0
UNET D2 RampUpFraction=0.1
UNET D2 TimeSlices= 1
UNET D2 BCVolumeCheck=0
UNET D1D2 MaxIter= 0
UNET D1D2 ZTol=0.01
UNET D1D2 QTol=0.1
UNET D1D2 MinQTol=1
Write IC File= 0
Write IC File at Fixed DateTime=0
Write IC File at Sim End=0
Echo Input=False
Echo Parameters=False
Echo Output=False
Write Detailed= 0
HDF Write Warmup=0
HDF Write Time Slices=0
HDF Flush=0
HDF Face Node Velocities=0
HDF Compression= 1
HDF Chunk Size= 1
HDF Spatial Parts= 1
HDF Use Max Rows=0
HDF Fixed Rows= 1
Calibration Method= 0
Calibration Iterations= 20
Calibration Max Change=0.05
Calibration Tolerance=0.2
Calibration Maximum=1.5
Calibration Minimum=0.5
Calibration Optimization Method= 1
WQ AD Non Conservative
WQ ULTIMATE=-1
WQ Max Comp Step=1HOUR
WQ Output Interval=15MIN
WQ Output Selected Increments= 0
WQ Output face flow=0
WQ Output face velocity=0
WQ Output face area=0
WQ Output face dispersion=0
WQ Output cell volume=0
WQ Output cell surface area=0
WQ Output cell continuity=0
WQ Output cumulative cell continuity=0
WQ Output face conc=0
WQ Output face dconc_dx=0
WQ Output face courant=0
WQ Output face peclet=0
WQ Output face adv mass=0
WQ Output face disp mass=0
WQ Output cell mass=0
WQ Output cell source sink temp=0
WQ Output nsm pathways=0
WQ Output nsm derived pathways=0
WQ Output MaxMinRange=-1
WQ Daily Max Min Mean=-1
WQ Daily Range=0
WQ Daily Time=0
WQ Create Restart=0
WQ Fixed Restart=0
WQ System Summary=0
WQ Write To DSS=0
WQ Use Fixed Temperature=0
Sorting and Armoring Iterations= 10
XS Update Threshold= 0.02
Bed Roughness Predictor= 0
Hydraulics Update Threshold= 0.02
Energy Slope Method= 1
Volume Change Method= 1
Sediment Retention Method= 0
XS Weighting Method= 0
Number of US Weighted Cross Sections= 1
Number of DS Weighted Cross Sections= 1
Upstream XS Weight=0
Main XS Weight=1
Downstream XS Weight=0
Number of DS XS's Weighted with US Boundary= 1
Upstream Boundary Weight= 1
Weight of XSs Associated with US Boundary= 0
Number of US XS's Weighted with DS Boundary= 1
Downstream Boundary Weight= 0.5
Weight of XSs Associated with DS Boundary= 0.5
Percentile Method= 0
Sediment Output Level= 3
Mass or Volume Output= 0
Output Increment Type= 1
Profile and TS Output Increment= 1
XS Output Flag= 0
XS Output Increment= 10
Write Gradation File= 0
Read Gradation Hotstart= 0
Write HDF5 File= 1
Write Binary Output= 1
Write DSS Sediment File= 0
SV Curve= 0
Specific Gage Flag= 0

--- MILLERRN.f01 (steady flow) ---

Flow Title=Flows
Program Version=5.07
Number of Profiles= 6
Profile Names=P100yr,P10yr,P25yr,P50yr,P500yr,P101yr
River Rch & RM=MILLERRN,Main            ,21374
     538     252     356     444     788     655
River Rch & RM=MILLERRN,Main            ,20044
     981     455     646     809    1446    1194
River Rch & RM=MILLERRN,Main            ,19422
    1095     507     720     902    1616    1333
River Rch & RM=MILLERRN,Main            ,13574
    1219     564     801    1004    1801    1483
River Rch & RM=MILLERRN,Main            ,9290
    1396     644     916    1149    2065    1699
Boundary for River Rch & Prof#=MILLERRN,Main            , 1
Up Type= 0
Dn Type= 3
Dn Slope=0.0098
Boundary for River Rch & Prof#=MILLERRN,Main            , 2
Up Type= 0
Dn Type= 3
Dn Slope=0.0098
Boundary for River Rch & Prof#=MILLERRN,Main            , 3
Up Type= 0
Dn Type= 3
Dn Slope=0.0098
Boundary for River Rch & Prof#=MILLERRN,Main            , 4
Up Type= 0
Dn Type= 3
Dn Slope=0.0098
Boundary for River Rch & Prof#=MILLERRN,Main            , 5
Up Type= 0
Dn Type= 3
Dn Slope=0.0098
Boundary for River Rch & Prof#=MILLERRN,Main            , 6
Up Type= 0
Dn Type= 3
Dn Slope=0.0098
DSS Import GetInterval= 0
DSS Import GetPeak= 0
DSS Import FillOption= 0

--- MILLERRN.g01 (geometry) ---

Geom Title=Geometry
Program Version=5.07

River Reach=MILLERRN        ,Main
Reach XY= 30
     2476115.061      572110.898     2476008.806       572574.29
     2475641.283       572823.43     2475692.236       573168.32
     2475260.986      573617.842     2475224.689      573914.442
     2475048.144      573969.753     2474140.734      575261.002
     2473623.748      575373.417     2473316.129      576692.655
     2472906.073      577226.429     2472372.988      577502.125
     2472334.923       578198.31     2472083.855      578707.068
     2471710.273      578969.426     2471062.919      580058.527
     2470944.857       580543.65     2471180.275      580999.136
     2471115.774      581723.287     2470049.189      582825.394
     2469601.835      583941.836     2469046.349      584393.601
     2468656.468      585231.974     2468588.263       585898.94
2468308.97675961586138.5010664092467920.09783266585827.804304933
2467704.45444631585945.3599009672467559.66029991586163.635462588
2467630.00838767586358.886965488     2466373.164      587794.122

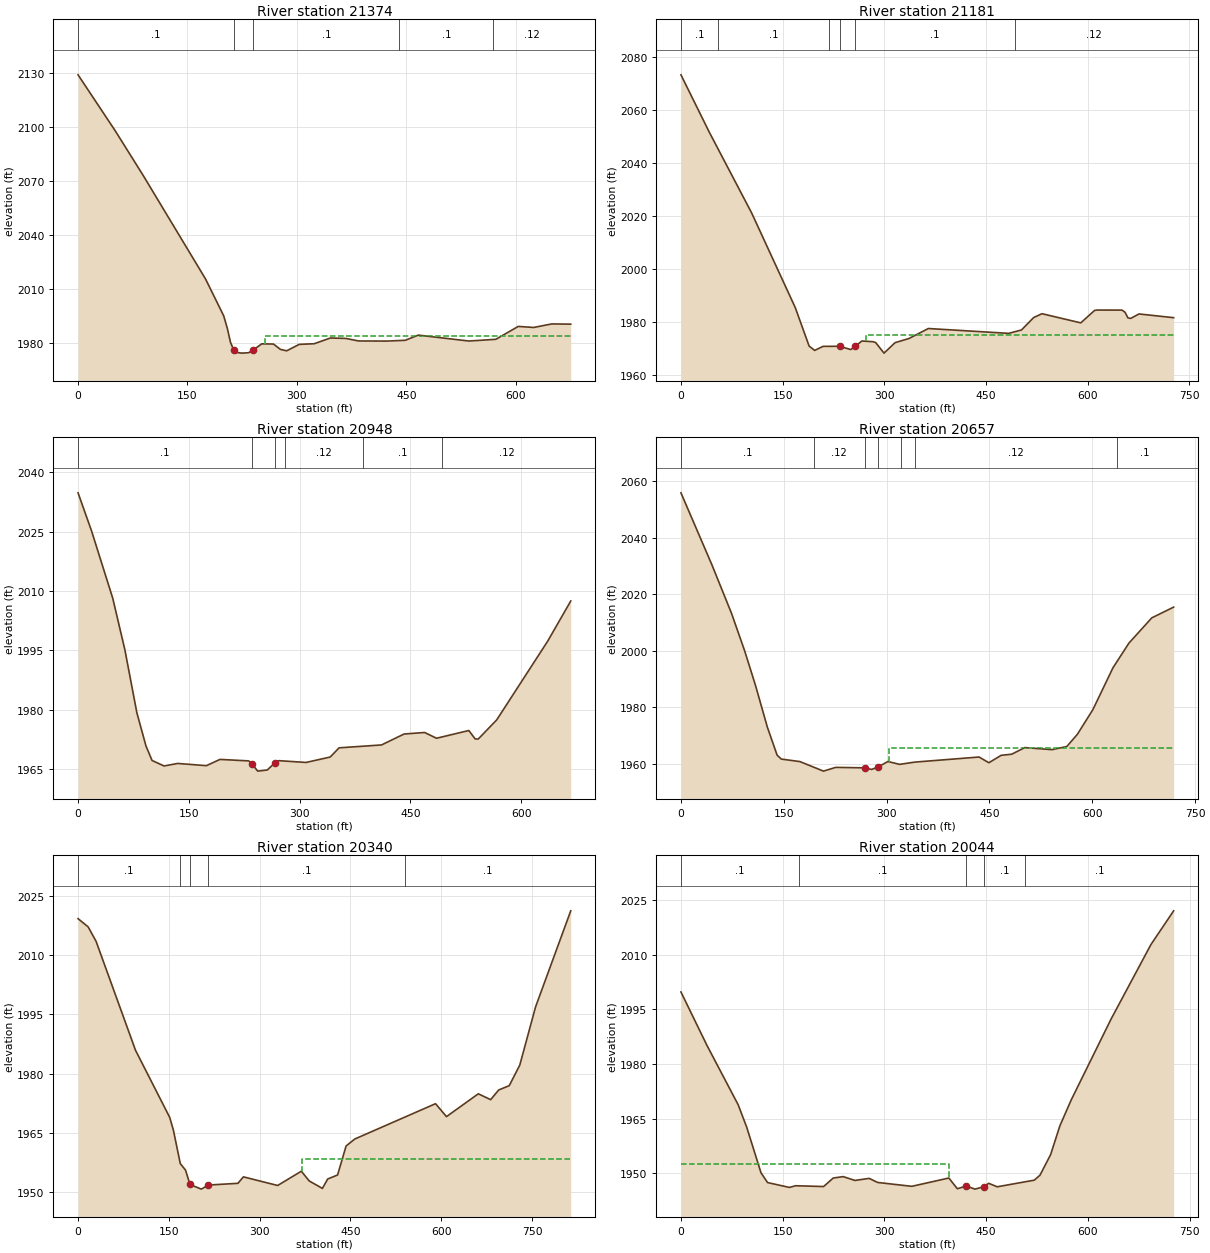
Type RM Length L Ch R = 1 ,21374   ,194.2,193.3,189.6
XS GIS Cut Line= 2
2475895.29458945572036.8534522152476526.77131151572276.387630531
#Sta/Elev= 30
       0 2128.87    50.8 2097.87    89.3 2072.94   174.8 2015.39   199.7 1994.89
   204.8 1987.68     209 1980.15   213.3 1976.07   217.6 1974.56   224.5 1974.19
   233.8 1974.41     240 1975.88   251.8 1979.34   267.9 1979.24   277.5 1976.26
     286 1975.48   303.2 1979.05   323.7 1979.41   345.9  1982.6   367.1 1982.36
   384.4 1980.96     423 1980.88   448.6 1981.32   466.4  1984.2   535.8 1980.91
   572.7 1981.87   603.5 1989.04   624.6 1988.45   649.4 1990.42   675.4  1990.3
#Mann= 5 ,-1 , 0
       0      .1       0   213.3    .045       0     240      .1       0
  440.58      .1       0   569.3     .12       0
#XS Ineff= 2 , 0
                          255.94         1983.71
Permanent Ineff=
       F       F
Bank Sta=213.3,240
XS Rating Curve= 0 ,0
Exp/Cntr=0.3,0.1

Type RM Length L Ch R = 1 ,21181   ,230,232.4,227.8
XS GIS Cut Line= 2
2475861.72714664572248.095322752 2476572.7149932572399.183231293
#Sta/Elev= 30
       0  2073.4    41.9 2051.71   104.4 2021.21   168.7 1985.51   189.1 1971.01
   197.3 1969.36   209.6 1970.89   234.1 1970.93   250.5 1969.69   257.3  1970.9
   266.8 1972.91   283.2 1972.66   287.3 1972.33   299.6 1968.34   315.9 1972.29
   336.4 1973.86     365 1977.63   483.6  1975.8   502.4 1977.08   520.4 1981.78
   532.7 1983.22   589.9 1979.76   610.3 1984.47   614.4  1984.6   650.8 1984.58
   655.3 1983.74   659.4 1981.66   663.5 1981.44   675.8 1983.13   726.9 1981.72
#Mann= 6 ,-1 , 0
       0      .1       0   55.02      .1       0  218.31      .1       0
   234.1    .045       0   257.3      .1       0  492.66     .12       0
#XS Ineff= 2 , 0
                          272.66         1975.29
Permanent Ineff=
       F       F
Bank Sta=234.1,257.3
XS Rating Curve= 0 ,0
Exp/Cntr=0.3,0.1

Type RM Length L Ch R = 1 ,20948   ,283.6,291.1,299.5
XS GIS Cut Line= 2
2475780.78935903572436.743091459 2476433.2907483572576.254917611
#Sta/Elev= 30
       0  2034.8    18.4 2025.12      47 2008.18    63.4  1995.2    79.7 1979.24
      92  1970.9   100.2 1967.24   116.5 1965.85   134.9 1966.49   173.8 1965.93
   192.2 1967.51   231.1 1967.13   235.2 1966.46   243.3 1964.55   256.2 1964.83
   266.3 1966.59     272 1967.19   308.8 1966.74   341.5 1968.11   353.5 1970.43
     411 1971.16   441.5 1973.92   469.4  1974.3   485.4 1972.85   529.2  1974.8
   537.8 1972.67   541.9 1972.65   566.9 1977.47     636 1997.36   667.2 2007.49
#Mann= 6 ,-1 , 0
       0      .1       0   235.2    .045       0   266.3      .1       0
  279.77     .12       0  386.36      .1       0  492.94     .12       0
Bank Sta=235.2,266.3
XS Rating Curve= 0 ,0
Exp/Cntr=0.3,0.1

Type RM Length L Ch R = 1 ,20657   ,320.7,317.1,308.9
XS GIS Cut Line= 2
2475616.66549206 572530.652153442476221.58449206572918.710091459
#Sta/Elev= 30
       0  2055.8    44.9 2030.51    73.8 2013.18    92.8 2000.03   108.8 1987.68
     126 1972.99   140.3 1963.04   146.4 1961.66   173.6 1960.77   207.9  1957.4
   225.8 1958.73     268 1958.56   278.1    1958   287.6 1958.88   301.9  1960.8
     319 1959.79   341.2 1960.59   434.9 1962.39   449.2 1960.37   467.2    1963
   482.5 1963.38   501.5 1965.72   541.2    1965   562.9 1966.11   578.3 1970.43
     601 1979.19   630.1  1993.9   653.5 2002.67   686.8 2011.59   718.7 2015.39
#Mann= 7 ,-1 , 0
       0      .1       0  194.03     .12       0     268    .045       0
   287.6     .12       0  321.19      .1       0   341.2     .12       0
  635.53      .1       0
#XS Ineff= 2 , 0
                          303.16         1965.66
Permanent Ineff=
       F       F
Bank Sta=268,287.6
XS Rating Curve= 0 ,0
Exp/Cntr=0.3,0.1

Type RM Length L Ch R = 1 ,20340   ,294,296.7,287.2
XS GIS Cut Line= 2
2475439.36997732572795.6631693122476188.22824036573114.744993198
#Sta/Elev= 30
       0 2019.16    16.7 2017.08    29.8 2013.43      95 1985.87   151.4 1968.93
   157.5 1965.71   168.9 1957.24   177.6 1955.59   184.9 1951.96   203.7 1950.78
   215.4 1951.81   264.2 1952.25   273.2 1953.88   329.8  1951.7   368.9 1955.31
   381.9 1952.85   403.7 1950.96   412.4 1953.33   428.8 1954.36   442.8 1961.68
   457.2 1963.45   590.6 1972.38   608.7 1969.11   661.3 1974.88   681.7  1973.4
     695 1975.85   712.4 1976.94   729.8 1982.14   755.9 1996.86     814 2021.14
#Mann= 5 ,-1 , 0
       0      .1       0  168.35      .1       0   184.9    .045       0
   215.4      .1       0  540.04      .1       0
#XS Ineff= 2 , 0
                          370.39         1958.47
Permanent Ineff=
       F       F
Bank Sta=184.9,215.4
XS Rating Curve= 0 ,0
Exp/Cntr=0.3,0.1

Type RM Length L Ch R = 1 ,20044   ,231.8,243.4,248.1
XS GIS Cut Line= 2
2475278.31257672573018.9479176112475970.63484203573238.813510204
#Sta/Elev= 30
       0 1999.79    38.2 1985.18    84.4 1968.82      97 1962.65     118 1950.17
   127.7 1947.47   159.9 1946.14   169.1  1946.6   210.3 1946.38   224.5 1948.71
   239.2 1949.11   256.5 1948.05   277.5 1948.62     290  1947.5   340.4 1946.44
     395 1948.72   407.5 1945.78   420.8 1946.52   433.5 1945.67   446.2 1946.31
   453.7 1947.27   466.3 1946.31   520.9 1948.13   529.3 1949.48     545 1955.13
   558.6 1963.01   575.4 1970.16   634.1 1992.33   692.9  2012.8   726.4 2022.06
#Mann= 5 ,-1 , 0
       0      .1       0  173.32      .1       0   420.8    .045       0
   446.2      .1       0  507.21      .1       0
#XS Ineff= 2 , 0
          394.93  1952.5
Permanent Ineff=
       F       F
Bank Sta=420.8,446.2
XS Rating Curve= 0 ,0
Exp/Cntr=0.3,0.1

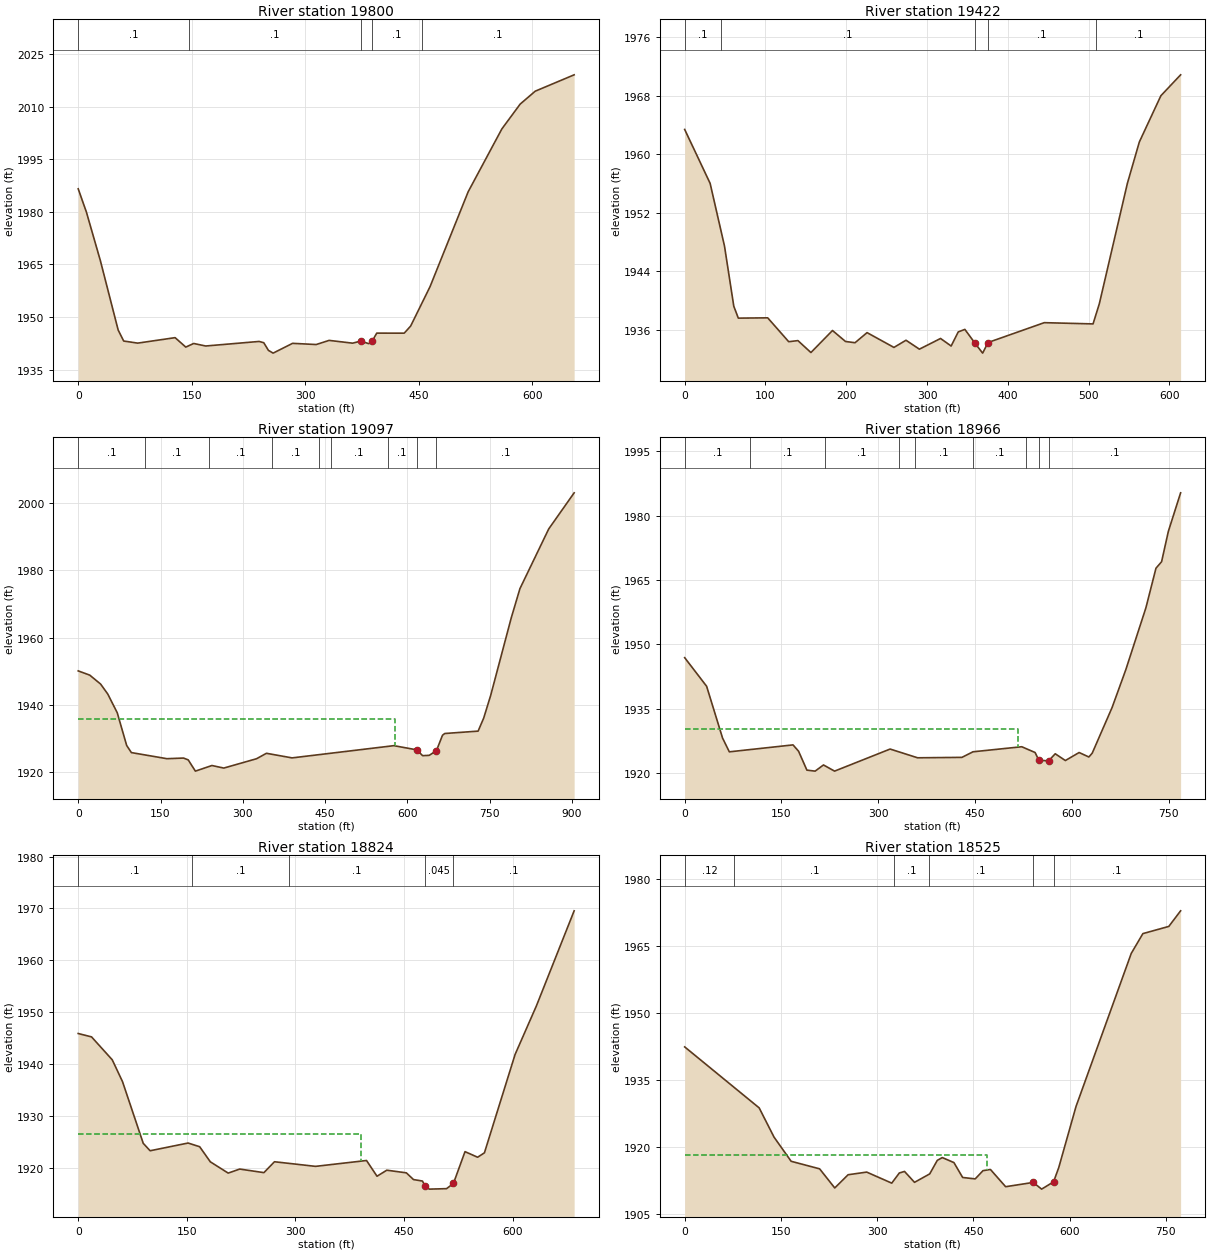
Type RM Length L Ch R = 1 ,19800   ,375.5,378.6,379.6
XS GIS Cut Line= 2
2475246.54290854573071.9100022682475745.31626077573496.854345427
#Sta/Elev= 30
       0 1986.56    10.8 1979.94    29.3 1966.06    52.8 1946.29    60.1 1943.17
    78.6 1942.57     128 1944.13   142.1 1941.44   152.6 1942.47   168.4 1941.75
     239 1943.05   245.1 1942.69   251.3 1940.51   257.5 1939.72   283.2 1942.51
   314.4 1942.17   331.5 1943.35   362.6 1942.56   373.4 1943.17   383.9 1942.41
   388.2 1943.09   394.4 1945.42   430.7 1945.41   439.2 1947.44   464.8 1958.66
   515.2 1985.72   559.7 2003.63   583.9 2010.71   603.8 2014.39   655.2 2019.05
#Mann= 5 ,-1 , 0
       0      .1       0  146.99      .1       0   373.4    .045       0
   388.2      .1       0  453.72      .1       0
Bank Sta=373.4,388.2
XS Rating Curve= 0 ,0
Exp/Cntr=0.3,0.1

Type RM Length L Ch R = 1 ,19422   ,332.7,324.3,310.7
XS GIS Cut Line= 2
2475077.80383069573298.0370801212475485.53685336573757.119510204
#Sta/Elev= 30
       0 1963.38    31.5 1956.02    49.3 1947.45    60.8 1939.24    66.4 1937.61
   102.8 1937.65   128.8 1934.39   140.2 1934.54   156.3 1932.91     183 1935.92
   199.1 1934.42   210.9 1934.25   225.8 1935.63   259.1 1933.61     274 1934.59
   290.6 1933.37   316.8 1934.83   329.9  1933.8   338.7 1935.73   346.9 1936.07
   359.6 1934.16   368.9 1932.83   375.6 1934.28   445.2 1936.99   505.6 1936.82
   513.4 1939.59   548.1 1956.02   562.9 1961.67   589.6 1967.99     614 1970.84
#Mann= 5 ,-1 , 0
       0      .1       0   45.37      .1       0   359.6    .045       0
   375.6      .1       0   509.4      .1       0
Bank Sta=359.6,375.6
XS Rating Curve= 0 ,0
Exp/Cntr=0.3,0.1

Type RM Length L Ch R = 1 ,19097   ,118.6,131.1,150.5
XS GIS Cut Line= 3
2474632.89302268573685.4201579752474985.15421168573828.166637588
2475504.79159713573892.816503401
#Sta/Elev= 30
       0 1950.09      21 1948.83    40.8 1946.17    53.8 1943.22    71.1 1937.64
    88.3 1927.89    96.9 1925.77   161.7 1923.95   191.9 1924.14   200.5 1923.59
   213.5 1920.25   243.7 1921.92   265.3 1921.16     325 1923.94     343 1925.56
   389.7 1924.19   575.2 1927.83     617 1926.58   627.6 1924.85   639.7 1924.95
   652.8 1926.36   663.8 1930.92   667.9 1931.45   728.7 1932.16   738.9 1936.05
   751.7 1942.85     789 1965.83   804.9 1974.57   857.3 1992.33   903.7  2003.1
#Mann= 9 ,-1 , 0
       0      .1       0  121.56      .1       0  237.76      .1       0
  353.95      .1       0  438.99      .1       0  460.29      .1       0
  563.77      .1       0     617    .045       0   652.8      .1       0
#XS Ineff= 2 , 0
          578.07 1935.89
Permanent Ineff=
       F       F
Bank Sta=617,652.8
XS Rating Curve= 0 ,0
Exp/Cntr=0.3,0.1

Type RM Length L Ch R = 1 ,18966   ,142.8,142.3,123.4
XS GIS Cut Line= 3
2474654.18546493573715.4630812892475117.12188986573894.939972187
2475290.90110168574104.329678234
#Sta/Elev= 30
       0 1946.86      34 1940.19    58.7 1928.11    69.2 1924.89   167.9 1926.51
   176.5 1925.04   189.4 1920.62   202.2 1920.39   215.1 1921.83   232.3 1920.39
   318.4 1925.54     361  1923.5   429.7  1923.6   446.8  1924.9   522.4 1926.08
   543.1 1924.73   548.9 1922.92     564 1922.79   574.3 1924.44     590 1922.86
   611.3 1924.73   626.4 1923.69   631.6 1924.58   662.4 1935.23   683.6 1944.03
   714.8 1958.49   730.4 1967.73   739.1 1969.24   749.6 1976.33   768.6 1985.32
#Mann= 9 ,-1 , 0
       0      .1       0  101.67      .1       0  216.82      .1       0
  331.97      .1       0  356.43      .1       0  447.12      .1       0
  528.49      .1       0   548.9    .045       0     564      .1       0
#XS Ineff= 2 , 0
          517.19 1930.26
Permanent Ineff=
       F       F
Bank Sta=548.9,564
XS Rating Curve= 0 ,0
Exp/Cntr(USF)=0,0
Exp/Cntr=0.3,0.1

Type RM Length L Ch R = 1 ,18824   ,297.9,298.4,292
XS GIS Cut Line= 2
2474627.28267271573732.0335903252475202.84939834574103.082238095
#Sta/Elev= 30
       0 1945.89    18.4 1945.24      47 1940.82    61.2  1936.6    89.8 1924.71
    99.3 1923.28   151.7 1924.77   167.7 1924.06   182.4 1921.15   207.1 1918.97
     223 1919.75   256.4 1919.06     271 1921.16   327.7 1920.27   398.1  1921.4
   412.6 1918.37   426.1 1919.53   453.1 1919.02     463 1917.72   475.3 1917.44
   479.1 1916.47   484.8 1915.88   508.6 1915.97   518.1 1916.97   534.1 1923.11
   551.5 1922.03   560.9 1922.88   603.2 1941.83   632.8 1951.26   684.8 1969.55
#Mann= 5 ,-1 , 0
       0      .1       0  157.35      .1       0  291.03      .1       0
   479.1    .045       0   518.1      .1       0
#XS Ineff= 2 , 0
          390.53  1926.5
Permanent Ineff=
       F       F
Bank Sta=479.1,518.1
XS Rating Curve= 0 ,0
Exp/Cntr=0.3,0.1

Type RM Length L Ch R = 1 ,18525   ,371.4,380.9,383
XS GIS Cut Line= 2
2474424.26651247 573996.931423282475106.69076871 574359.86100907
#Sta/Elev= 30
       0 1942.32   116.1 1928.67   139.3 1922.12   165.9 1916.72   210.3 1915.03
   233.9 1910.75   254.7 1913.71   283.7  1914.3   322.7 1911.83   334.5  1914.1
   342.6 1914.45   358.2 1912.01   381.9  1913.9   393.7 1916.93   401.5 1917.55
   419.6 1916.43   433.2  1913.1   452.8 1912.78   464.9 1914.62   476.5 1914.89
   500.2 1911.03   543.2 1911.99   556.3 1910.49   574.9 1912.12     583 1915.32
   609.9 1928.99     696 1963.25   714.1 1967.67   754.5 1969.28   772.9 1972.77
#Mann= 6 ,-1 , 0
       0     .12       0   77.54      .1       0  326.96      .1       0
  380.41      .1       0   543.2    .045       0   574.9      .1       0
#XS Ineff= 2 , 0
          470.94 1918.04
Permanent Ineff=
       F       F
Bank Sta=543.2,574.9
XS Rating Curve= 0 ,0
Exp/Cntr=0.3,0.1

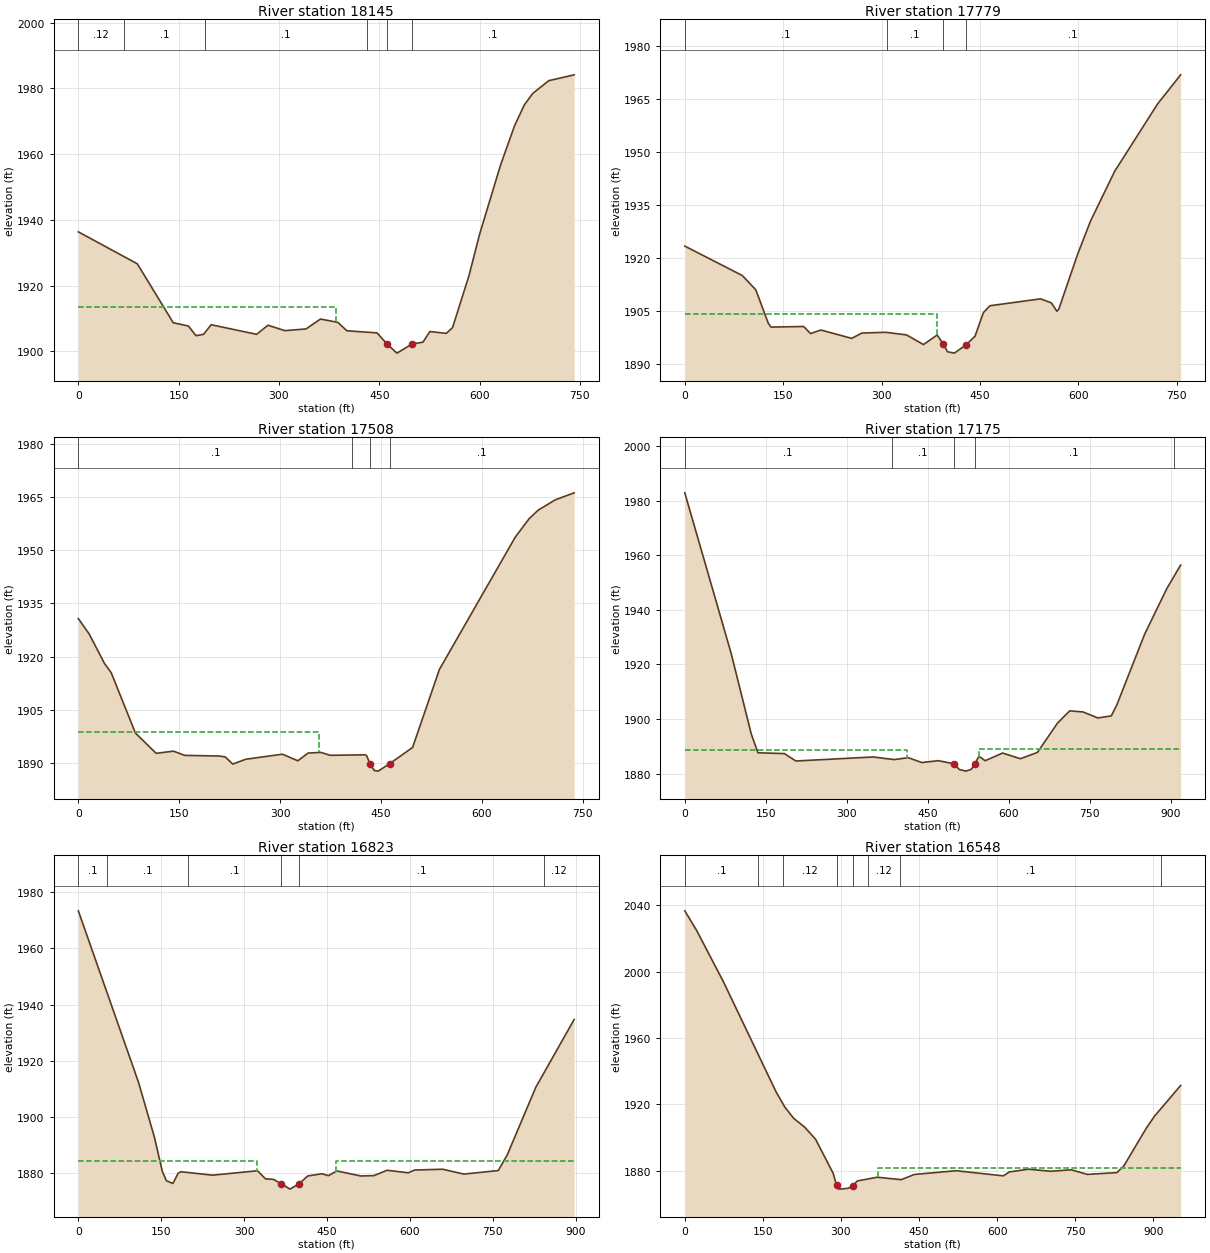
Type RM Length L Ch R = 1 ,18145   ,366.1,365.1,362.1
XS GIS Cut Line= 2
2474330.08076417574186.8285812552474855.65934543574709.778178382
#Sta/Elev= 30
       0 1936.34    88.2 1926.61   141.9 1908.69   164.6 1907.69   175.9 1904.75
   187.2 1905.15   198.6 1908.08   266.6 1905.16   283.6 1907.93   308.8 1906.28
   340.4  1906.8   362.1 1909.81     388  1908.8   401.6 1906.24   446.7  1905.6
   461.5 1902.22   476.5 1899.44   499.1 1902.22   515.3 1902.78   525.7 1906.01
   550.2 1905.45   559.6 1907.21   584.2 1923.06   600.1 1935.67   631.3 1956.63
   652.3 1968.61   666.8 1974.92   679.3 1978.41   703.3 1982.32   741.4 1984.11
#Mann= 6 ,-1 , 0
       0     .12       0   68.07      .1       0  189.11      .1       0
  431.19      .1       0   461.5    .045       0   499.1      .1       0
#XS Ineff= 2 , 0
           385.4 1913.45
Permanent Ineff=
       F       F
Bank Sta=461.5,499.1
XS Rating Curve= 0 ,0
Exp/Cntr=0.3,0.1

Type RM Length L Ch R = 1 ,17779   ,271.8,271.5,270.2
XS GIS Cut Line= 2
     2474115.694      574534.4852474695.24033862575020.031004535
#Sta/Elev= 30
       0 1923.36    87.8 1915.03   108.3 1910.99   127.4 1901.51   131.4 1900.46
   181.3 1900.62   191.8 1898.62   207.5 1899.63   254.5 1897.26   270.1 1898.77
   306.3 1898.98     338 1898.25     364 1895.51   384.9 1898.22   394.3 1895.61
   400.6 1893.48     411 1893.09   428.4 1895.35   442.6 1897.88   455.3 1904.53
   465.3 1906.49   542.5 1908.44     559  1907.3   567.4 1904.94   570.3 1905.51
   598.7 1920.88   618.6  1930.4   655.5  1944.5   720.8 1963.52   756.1  1971.8
#Mann= 4 ,-1 , 0
       0      .1       0  308.22      .1       0   394.3    .045       0
   428.4      .1       0
#XS Ineff= 2 , 0
          384.22 1904.29
Permanent Ineff=
       F       F
Bank Sta=394.3,428.4
XS Rating Curve= 0 ,0
Exp/Cntr=0.3,0.1

Type RM Length L Ch R = 1 ,17508   ,323.3,333.4,336.4
XS GIS Cut Line= 2
2473928.61216931574738.2734187452474502.90092668575200.430091458
#Sta/Elev= 30
       0  1930.7    16.2 1926.36    38.9 1918.06    48.9 1915.45    84.9 1898.44
   115.7 1892.73   141.4 1893.34   158.4 1892.15   209.6 1891.97   218.4 1891.71
   229.6  1889.7   249.2 1891.07   303.5 1892.48   326.4 1890.63   341.6  1892.8
   360.4 1892.99   374.6 1892.17   425.9 1892.31   428.5 1892.14     434 1889.59
   440.1 1887.89   445.8 1887.71   462.8  1889.8     497 1894.39   536.9 1916.39
   649.7 1953.69   670.2 1958.85   683.7 1961.27   709.2 1964.19   737.2 1966.16
#Mann= 4 ,-1 , 0
       0      .1       0  407.37      .1       0     434    .045       0
   462.8      .1       0
#XS Ineff= 2 , 0
          357.89 1898.85
Permanent Ineff=
       F       F
Bank Sta=434,462.8
XS Rating Curve= 0 ,0
Exp/Cntr=0.3,0.1

Type RM Length L Ch R = 1 ,17175   ,340.7,351.9,350.4
XS GIS Cut Line= 2
2473783.01091602574877.867109851      2474350.46      575599.462
#Sta/Elev= 30
       0 1982.93      86 1923.93     123 1894.52   135.5  1887.6   184.5  1887.3
   205.6 1884.58     349 1886.06   387.8  1885.1   413.5 1885.81   438.9 1884.01
   469.5 1884.71     499 1883.53   507.9 1881.51   520.3 1880.87   530.4 1881.53
   536.7 1883.33   544.6 1886.34   556.1 1884.69   588.4  1887.5   621.5 1885.42
   652.9 1887.74   689.9 1898.44   712.7 1902.98   737.3 1902.57   764.6 1900.38
   789.6 1901.11   800.2  1905.3   851.1 1930.96   892.1 1947.69     918 1956.43
#Mann= 5 ,-1 , 0
       0      .1       0  382.85      .1       0     499    .045       0
   536.7      .1       0  905.24     .12       0
#XS Ineff= 2 , 0
          411.07 1888.55  543.81         1888.95
Permanent Ineff=
       F       F
Bank Sta=499,536.7
XS Rating Curve= 0 ,0
Exp/Cntr=0.3,0.1

Type RM Length L Ch R = 1 ,16823   ,277.2,274.2,246.5
XS GIS Cut Line= 2
2473631.25398547575055.9207285632474123.89282389575805.650083984
#Sta/Elev= 30
       0 1973.39   108.9 1912.42   137.6 1892.95     152 1880.72   159.3 1877.43
   171.1 1876.45   180.6 1880.06   185.4 1880.63   242.9  1879.4   324.2 1880.97
   338.6 1878.11     353  1877.9   367.3 1876.35     383 1874.44   399.7 1876.42
   415.2 1879.12   440.8 1879.91   452.4 1879.23   467.8  1880.9   510.9 1879.12
   534.8 1879.24   558.8 1881.15     597 1880.25   608.3 1881.23   659.3 1881.51
   697.6 1879.79   759.8 1881.04   775.9 1886.56   827.8 1910.68   897.1 1934.76
#Mann= 6 ,-1 , 0
       0      .1       0    51.1      .1       0  198.92      .1       0
   367.3    .045       0   399.7      .1       0  841.91     .12       0
#XS Ineff= 2 , 0
          323.09 1884.49  465.44         1884.49
Permanent Ineff=
       F       F
Bank Sta=367.3,399.7
XS Rating Curve= 0 ,0
Exp/Cntr=0.3,0.1

Type RM Length L Ch R = 1 ,16548   ,390.6,391,386.2
XS GIS Cut Line= 3
2473324.39771403575320.180289158 2473787.9359628 575475.37513891
2474098.59820837575819.877234232
#Sta/Elev= 30
       0 2036.61      23 2024.65    74.2 1993.89   175.4 1927.55   192.3 1918.34
   209.2 1911.63   230.3 1906.31   251.4 1898.96   285.1 1878.49   291.6 1871.29
   293.5 1869.37   297.8 1868.97   314.6 1869.51   323.1 1871.11   331.5 1873.89
   369.5 1876.13   415.9 1874.68   441.2 1877.81   521.6 1880.06   612.1 1876.96
   623.6 1879.32   660.4 1880.97   702.9 1879.73   742.5  1880.6   773.6 1877.84
   830.3 1878.93   843.7    1883   887.2 1905.93   902.9 1913.05   952.7 1931.39
#Mann= 8 ,-1 , 0
       0      .1       0   140.5      .1       0  189.13     .12       0
   291.6    .045       0   323.1      .1       0  352.88     .12       0
  413.52      .1       0   915.4     .12       0
#XS Ineff= 2 , 0
                          370.33         1881.62
Permanent Ineff=
       F       F
Bank Sta=291.6,323.1
XS Rating Curve= 0 ,0
Exp/Cntr=0.3,0.1

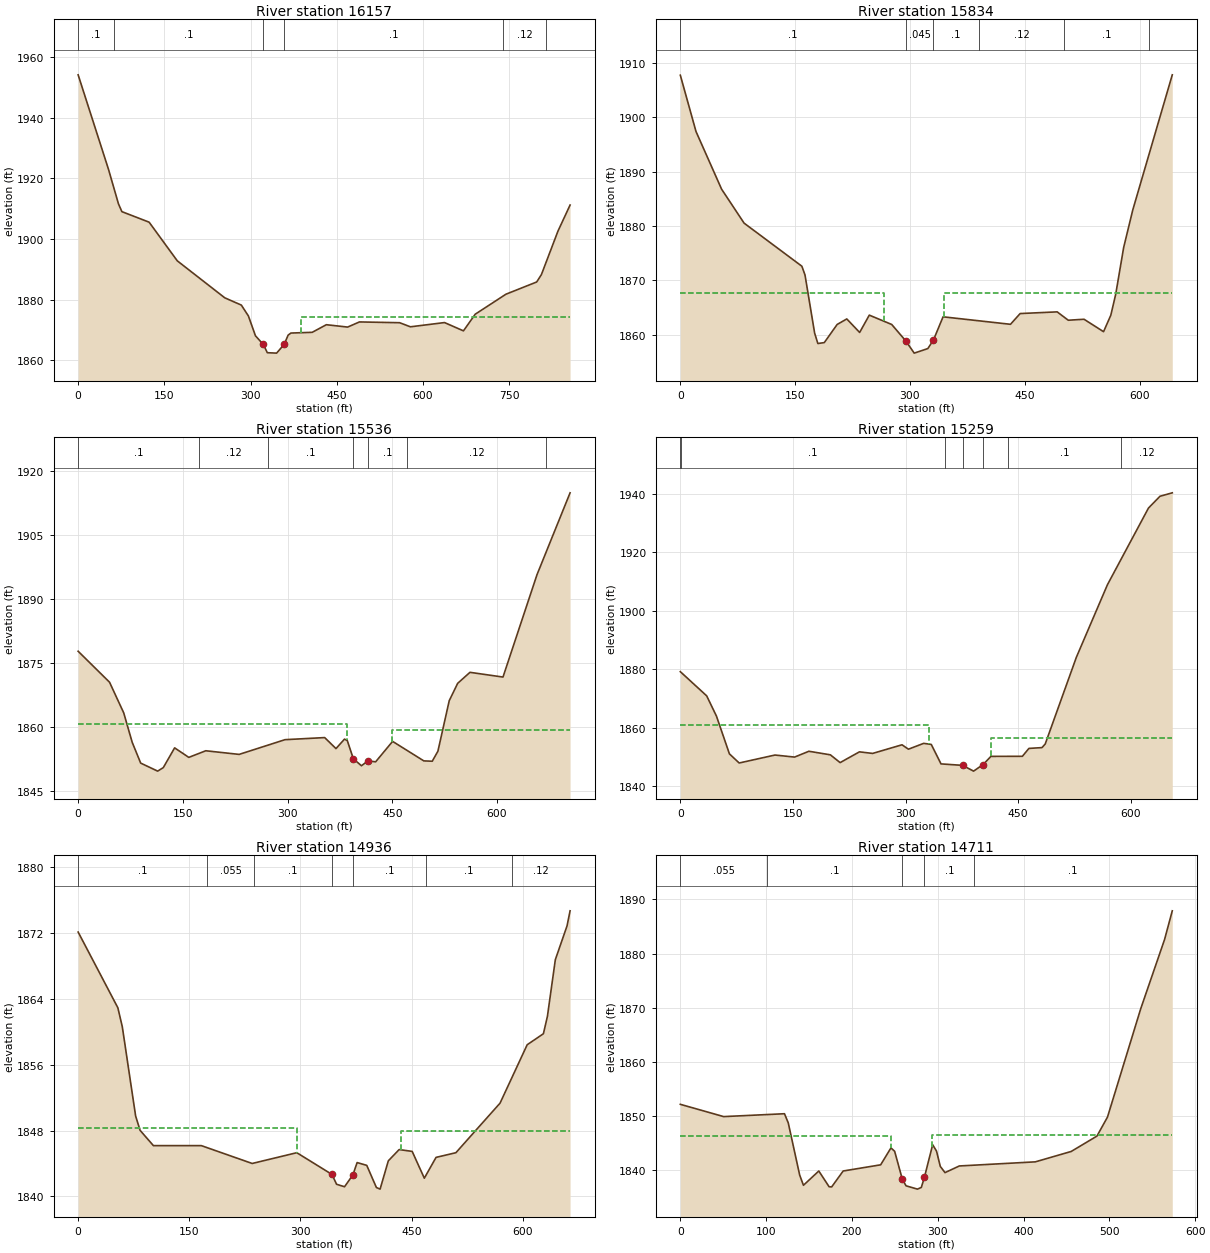
Type RM Length L Ch R = 1 ,16157   ,320.2,323.6,322.6
XS GIS Cut Line= 2
2473198.53234408575715.4847948272474031.30798866575912.714534728
#Sta/Elev= 30
       0 1954.22    52.9 1922.97    70.1 1911.66    76.1 1909.05   123.5 1905.57
   172.5 1892.81   255.1  1880.6   283.9  1878.2   296.2 1874.61   308.5 1868.05
   322.1 1865.21   329.1 1862.48   345.3 1862.34   358.6 1865.28   365.3 1868.28
   370.2 1868.97   407.2 1869.21   431.8 1871.72   468.8 1870.94   489.4 1872.64
   559.3 1872.38     578 1871.03   637.4 1872.43   670.3 1869.69   690.8 1875.19
   744.2 1881.79   797.7 1885.83   805.9 1888.26   834.7 1902.61   855.8 1911.23
#Mann= 6 ,-1 , 0
       0      .1       0    61.7      .1       0   322.1    .045       0
   358.6      .1       0  738.34     .12       0  814.38      .1       0
#XS Ineff= 2 , 0
                          387.24         1874.41
Permanent Ineff=
       F       F
Bank Sta=322.1,358.6
XS Rating Curve= 0 ,0
Exp/Cntr=0.3,0.1

Type RM Length L Ch R = 1 ,15834   ,304.5,297.4,289.1
XS GIS Cut Line= 2
2473151.35097452576004.5532376122473764.39376553576198.002998429
#Sta/Elev= 30
       0 1907.79    20.5 1897.41    53.9  1886.8    83.3 1880.54   158.8  1872.6
   162.9 1870.99   175.5 1860.27   179.7 1858.36   188.1 1858.53   204.9 1861.87
   217.5 1862.89   234.3  1860.4   246.9 1863.59   276.2 1861.87   294.7 1858.82
   305.6 1856.59   323.4 1857.43   330.7 1858.99   343.3 1863.28   431.4  1861.9
     444 1863.88   492.4 1864.19   506.9 1862.65   527.5 1862.83     553 1860.54
   562.5 1863.58   568.9 1867.45   579.3 1876.07   591.2 1882.98   642.8 1907.86
#Mann= 6 ,-1 , 0
       0      .1       0   294.7    .045       0   330.7      .1       0
  390.13     .12       0  501.32      .1       0  612.52     .12       0
#XS Ineff= 2 , 0
          265.88  1867.6  345.09          1867.6
Permanent Ineff=
       F       F
Bank Sta=294.7,330.7
XS Rating Curve= 0 ,0
Exp/Cntr=0.3,0.1

Type RM Length L Ch R = 1 ,15536   ,267.4,277.4,285
XS GIS Cut Line= 2
2472998.35785143576447.608166531 2473693.5730302576332.842871837
#Sta/Elev= 30
       0 1877.75      45 1870.49    65.3 1863.31    77.4 1856.43    89.6 1851.54
   113.9 1849.66     122 1850.49   138.2 1855.11   158.5 1852.88   182.8 1854.43
   230.6 1853.58   296.3 1857.03   353.1 1857.52   369.3 1854.94   381.5 1857.16
   385.5 1856.82   394.2 1852.54   405.8 1850.92     415 1852.06   426.1 1851.84
   450.4 1856.63   495.1 1852.06   507.2 1851.98   515.3 1854.33   531.5 1866.16
   543.6 1870.23   561.2 1872.81   608.5  1871.7   657.2 1895.68   704.6 1914.87
#Mann= 7 ,-1 , 0
       0      .1       0  173.13     .12       0  272.45      .1       0
   394.2    .045       0     415      .1       0  471.08     .12       0
  669.71      .1       0
#XS Ineff= 2 , 0
          385.26 1860.69  449.14         1859.39
Permanent Ineff=
       F       F
Bank Sta=394.2,415
XS Rating Curve= 0 ,0
Exp/Cntr=0.3,0.1

Type RM Length L Ch R = 1 ,15259   ,314.5,323.4,331.2
XS GIS Cut Line= 2
2472978.41554694576490.9836367352473582.92217551576744.278213878
#Sta/Elev= 30
       0 1879.16    35.1  1870.9    48.1 1863.99    65.4 1851.07    78.4 1847.95
   126.1 1850.67   152.2 1849.97   171.3 1851.96   199.9 1850.74   212.9 1848.08
   238.6 1851.76   256.2 1851.22   295.3 1854.17   303.9 1852.67   324.2 1854.66
   334.3  1854.3   347.3 1847.64   376.1 1847.14   390.7 1845.17   403.4 1847.43
   413.8 1850.21   455.7 1850.24   464.4 1852.93   481.8 1853.21   486.1 1854.43
   527.6 1884.07     569 1908.87   623.7 1935.09     639 1939.11   655.4 1940.29
#Mann= 7 ,-1 , 0
       0      .1       0    1.32      .1       0  352.44     .12       0
   376.1    .045       0   403.4     .12       0  436.67      .1       0
  586.53     .12       0
#XS Ineff= 2 , 0
          331.58 1861.02  414.25         1856.46
Permanent Ineff=
       F       F
Bank Sta=376.1,403.4
XS Rating Curve= 0 ,0
Exp/Cntr=0.3,0.1

Type RM Length L Ch R = 1 ,14936   ,232.8,224.6,218.5
XS GIS Cut Line= 2
2472906.98707298576631.0020383672473349.79695788577125.722027102
#Sta/Elev= 30
       0 1872.14    53.6 1862.93    59.6 1860.62    77.6 1849.76    83.6 1848.02
   101.6 1846.16   166.3 1846.16   234.9 1843.99   295.1  1845.3   342.5 1842.66
   348.8 1841.46   359.5 1841.16   370.8  1842.6   376.5  1844.1   389.5 1843.76
   402.5 1841.07   407.5 1840.87   418.6 1844.31   433.2 1845.68   450.8 1845.46
   467.2  1842.2     483 1844.73   509.8  1845.3   569.4 1851.33     606 1858.43
   627.9 1859.77   633.3 1861.88     644 1868.78   659.8 1872.89   663.9 1874.72
#Mann= 7 ,-1 , 0
       0      .1       0  174.44    .055       0  236.91      .1       0
   342.5    .045       0   370.8      .1       0   469.5      .1       0
   585.8     .12       0
#XS Ineff= 2 , 0
          295.35 1848.27  435.96         1847.91
Permanent Ineff=
       F       F
Bank Sta=342.5,370.8
XS Rating Curve= 0 ,0
Exp/Cntr=0.3,0.1

Type RM Length L Ch R = 1 ,14711   ,56.4,63.8,71.9
XS GIS Cut Line= 2
2472769.17517738576953.2949681262473286.83762748577199.800896746
#Sta/Elev= 30
       0 1852.14    50.5 1849.87   121.4  1850.4   125.8 1848.71   139.1 1839.07
   143.5 1837.18   161.4 1839.82   173.4 1836.91   176.4 1836.88   189.8 1839.82
   233.5 1840.96   245.5 1844.09   249.8 1843.46   258.7 1838.32   263.1 1837.08
   276.4 1836.47   280.9 1836.79   284.5 1838.66   294.1 1844.67   298.6  1843.5
     303 1840.67   308.5 1839.52   325.2 1840.75   413.8 1841.51   455.6 1843.43
   485.6 1846.27   497.9 1849.79   536.6 1869.79   564.4 1882.59   573.4 1887.89
#Mann= 5 ,-1 , 0
       0    .055       0  100.95      .1       0   258.7    .045       0
   284.5      .1       0  342.48      .1       0
#XS Ineff= 2 ,-1
       0  245.72 1846.21  293.31573.3582 1846.47
Permanent Ineff=
       F       F
Bank Sta=258.7,284.5
XS Rating Curve= 0 ,0
Exp/Cntr(USF)=0,0
Exp/Cntr=0.5,0.3

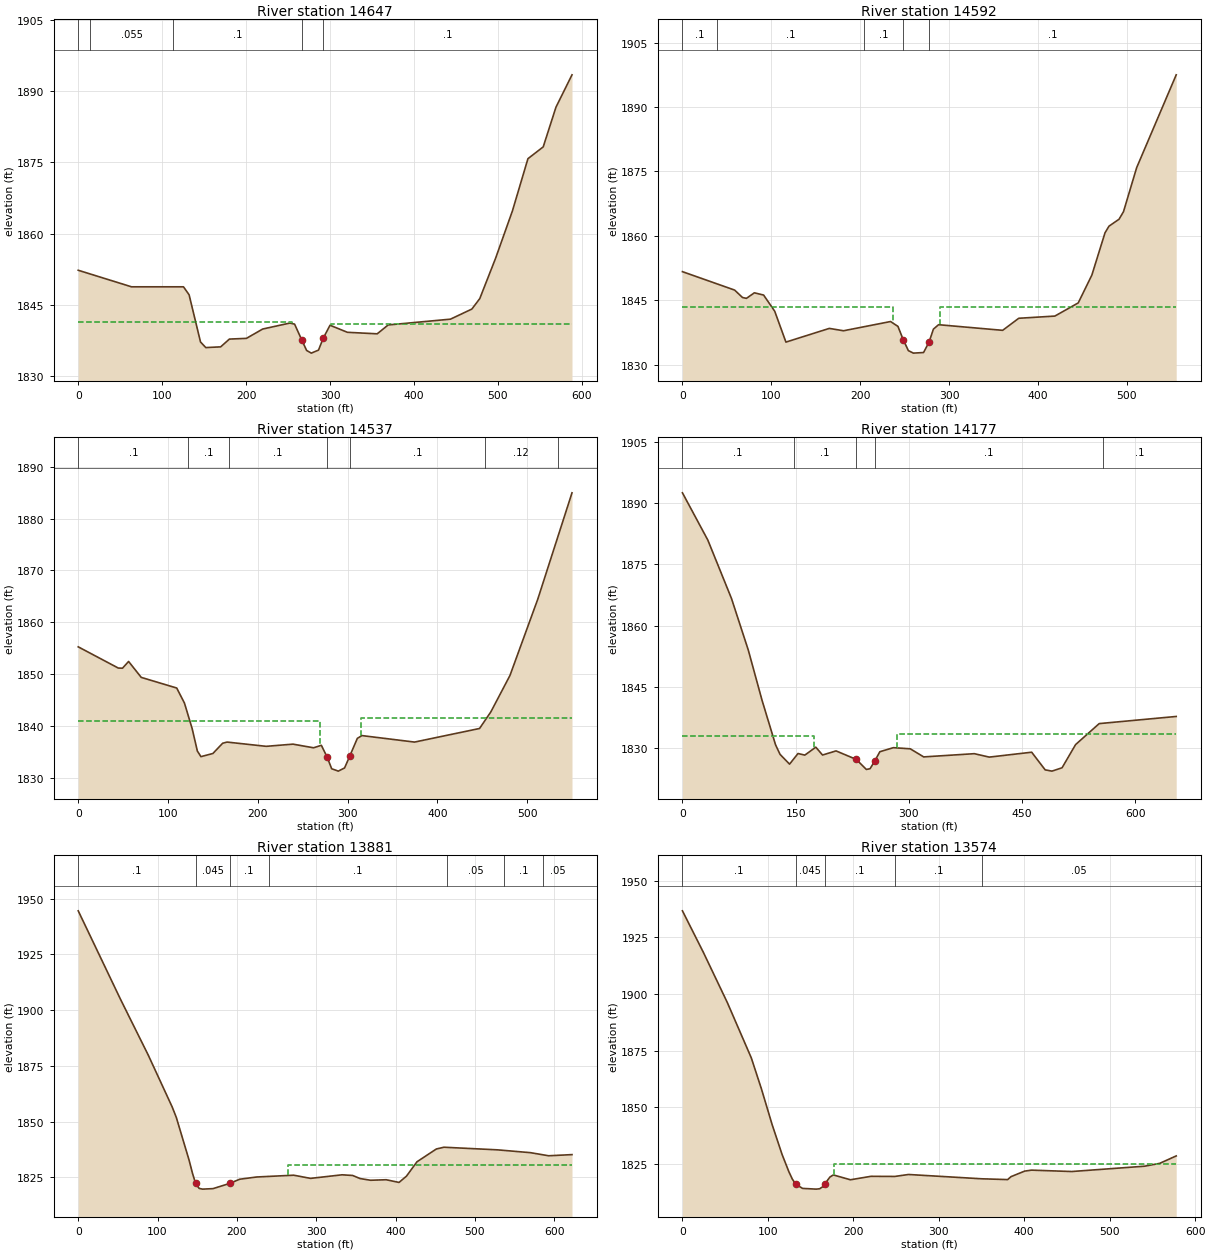
Type RM Length L Ch R = 1 ,14647   ,52.4,55.7,55.3
XS GIS Cut Line= 4
2472746.68577859576984.8807455672472966.37992028577104.279849406
2473013.62688993577161.7978994172473255.44119908577267.304781257
#Sta/Elev= 30
       0 1852.26    63.5 1848.77   125.4 1848.77   132.1 1847.09   145.7 1837.14
     152 1835.96   169.7 1836.11   180.1 1837.75   200.4  1837.9   219.8 1839.87
   252.2 1841.13   257.8  1840.9   266.3 1837.57   272.1 1835.36   277.7 1834.79
   286.3 1835.43   291.9 1837.93     300 1840.67   320.7 1839.18   356.2 1838.86
   369.3 1840.73   443.5 1841.95     469 1844.08   478.4 1846.28   497.3 1854.81
   517.3 1864.76   535.8 1875.78     554 1878.27   569.2 1886.64   588.3 1893.46
#Mann= 5 ,-1 , 0
       0      .1       0   13.86    .055       0  113.16      .1       0
   266.3    .045       0   291.9      .1       0
#XS Ineff= 2 , 0
          254.79  1841.3  301.07            1841
Permanent Ineff=
       F       F
Bank Sta=266.3,291.9
XS Rating Curve= 0 ,0
Exp/Cntr=0.5,0.3

Type RM Length L Ch R = 1 ,14592   ,61,54.1,48.5
XS GIS Cut Line= 4
2472733.81415174577037.9849803372472923.24138277577128.930442268
2472967.40702831577188.502708351 2473207.7938723 577313.87170624
#Sta/Elev= 30
       0 1851.63    58.7 1847.34    67.6  1845.6      72 1845.41    80.9  1846.7
    91.3 1846.18   103.8 1842.41   116.4 1835.22   165.2 1838.41   181.2 1837.86
   234.1 1840.01   242.4 1838.88   248.3 1835.81   254.1 1833.24   259.8 1832.65
   271.2 1832.79   277.3 1835.17   282.3 1838.24   288.1 1839.27   360.2 1837.96
   378.3 1840.77   418.9 1841.28   445.2 1844.35   460.5 1850.82   475.3 1860.67
   479.8 1862.23   491.1 1863.84   496.1  1865.6   510.9 1875.85   555.4 1897.48
#Mann= 5 ,-1 , 0
       0      .1       0    39.2      .1       0  204.38      .1       0
   248.3    .045       0   277.3      .1       0
#XS Ineff= 2 , 0
          237.17  1843.5  290.19         1843.36
Permanent Ineff=
       F       F
Bank Sta=248.3,277.3
XS Rating Curve= 0 ,0
Exp/Cntr=0.5,0.3

Type RM Length L Ch R = 1 ,14537   ,348.6,360.5,367.2
XS GIS Cut Line= 2
2472677.96922943577047.2034731762473131.74431406577357.975534277
#Sta/Elev= 30
       0 1855.27    44.6 1851.18    49.3 1851.15    56.1 1852.45    70.2 1849.38
   109.7 1847.33   118.3 1844.44   126.9 1839.51   132.7 1835.18   136.7  1834.1
     150 1834.71   160.9 1836.69   165.8 1836.91   209.4 1836.09   239.2 1836.51
   262.2 1835.81   270.8 1836.29   277.3    1834   282.3 1831.77   289.7 1831.31
   296.7 1831.93   302.5 1834.23   310.9 1837.63   316.1 1838.16   374.6 1836.91
     447 1839.53   459.6 1842.73   480.9 1849.75   511.9 1864.47     550 1884.96
#Mann= 7 ,-1 , 0
       0      .1       0  122.61      .1       0   168.1      .1       0
   277.3    .045       0   302.5      .1       0  452.87     .12       0
  534.15      .1       0
#XS Ineff= 2 , 0
          269.82 1841.02  314.74         1841.49
Permanent Ineff=
       F       F
Bank Sta=277.3,302.5
XS Rating Curve= 0 ,0
Exp/Cntr=0.3,0.1

Type RM Length L Ch R = 1 ,14177   ,307,295.7,267.9
XS GIS Cut Line= 2
2472495.26883069577148.7787072652472787.82486155      577734.248
#Sta/Elev= 30
       0 1892.52    33.7 1880.94      65 1866.67    87.3 1854.03   105.5 1841.76
   123.4 1830.86   129.4 1828.51     142 1826.12   153.2 1828.72   162.2 1828.33
   176.8 1830.27   185.7 1828.35   203.6 1829.36   230.4 1827.28   243.8 1824.82
   248.7    1825   254.6 1826.78   261.7 1829.16   279.6 1830.15     302 1829.87
   319.8 1827.89   386.9 1828.68   406.7 1827.84   462.9 1829.04   480.8 1824.72
   489.8 1824.41   503.2 1825.23   521.1  1830.9   552.4 1836.04   654.5 1837.79
#Mann= 5 ,-1 , 0
       0      .1       0  147.33      .1       0   230.4    .045       0
   254.6      .1       0  556.88      .1       0
#XS Ineff= 2 , 0
          174.86 1832.96  284.75         1833.54
Permanent Ineff=
       F       F
Bank Sta=230.4,254.6
XS Rating Curve= 0 ,0
Exp/Cntr=0.3,0.1

Type RM Length L Ch R = 1 ,13881   ,316.3,307.7,300.4
XS GIS Cut Line= 3
2472219.42109175577456.7886651432472526.74536114 577568.14338449
2472735.58420767577777.033826939
#Sta/Elev= 30
       0 1944.58    53.1 1905.04    88.4 1879.76   118.4 1856.63   123.6 1851.94
   139.7  1832.8   143.9 1827.01   147.9 1822.32   152.4  1820.1   156.7 1819.77
   169.8 1819.99   190.7 1822.31   203.5 1824.21   224.8 1825.21   271.6 1826.01
   292.8 1824.59   332.5 1826.19   345.8  1825.9   355.2 1824.52   368.4 1823.75
   388.2 1823.98   404.3 1822.77   413.7 1825.59   426.9 1832.03   451.3 1837.76
   460.9 1838.56   528.7 1837.38   570.2 1836.11   592.8 1834.73   622.3 1835.25
#Mann= 7 ,-1 , 0
       0      .1       0   147.9    .045       0   190.7      .1       0
  240.05      .1       0  464.64     .05       0  536.87      .1       0
  585.45     .05       0
#XS Ineff= 2 , 0
                          264.18         1830.74
Permanent Ineff=
       F       F
Bank Sta=147.9,190.7
XS Rating Curve= 0 ,0
Exp/Cntr=0.3,0.1

Type RM Length L Ch R = 1 ,13574   ,272.8,268.5,263.9
XS GIS Cut Line= 3
 2472138.1500609      577799.4472472565.93040702577795.888965388
     2472700.168      577863.164
#Sta/Elev= 30
       0 1936.66    24.6 1918.25    52.6 1896.12    80.6 1871.75    92.6 1857.88
   104.9 1842.39   116.6 1829.13   124.6 1821.48   128.6 1818.25   132.6    1816
   140.6 1814.13   156.6 1813.81   160.6 1813.97   164.6 1814.95     167 1816.29
   172.6 1819.13   176.6 1820.08   196.6 1817.94   220.6 1819.46   248.6 1819.41
   264.6 1820.27   350.3 1818.37   380.6 1818.02   384.6 1819.33   400.6 1821.77
   408.6 1822.19   455.6 1821.58   540.9 1823.93   558.5 1825.17   577.9 1828.47
#Mann= 5 ,-1 , 0
       0      .1       0   132.6    .045       0     167      .1       0
   248.6      .1       0   350.3     .05       0
#XS Ineff= 2 , 0
                          177.53         1824.79
Permanent Ineff=
       F       F
Bank Sta=132.6,167
XS Rating Curve= 0 ,0
Exp/Cntr=0.3,0.1