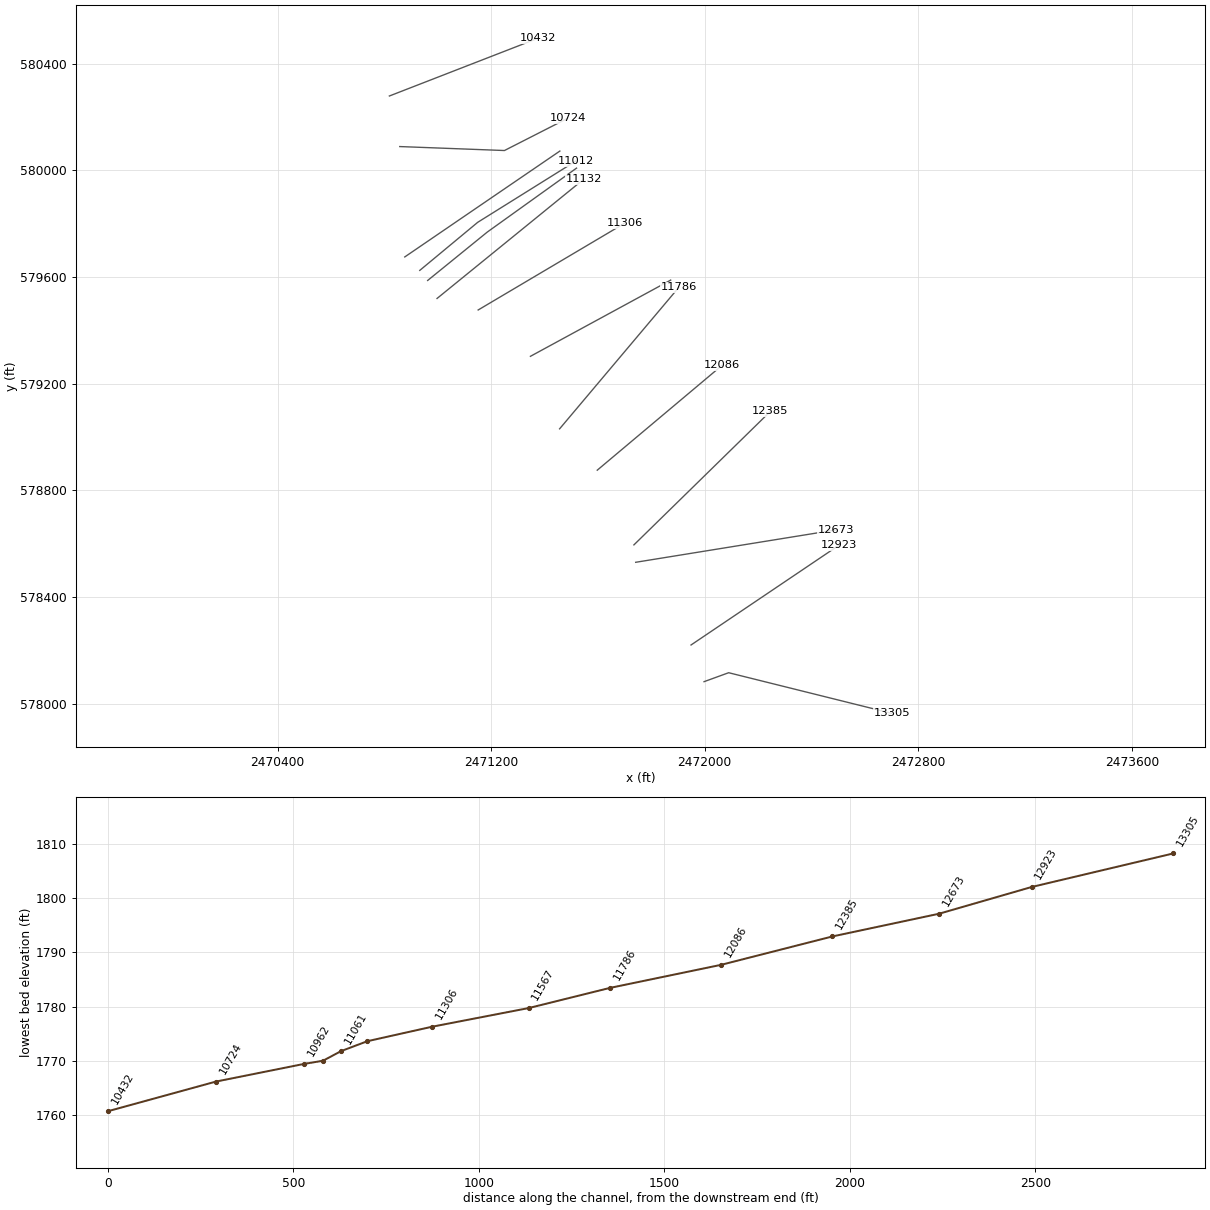
HEC-RAS study MILLERRN.prj: MILLERRN

--- MILLERRN.g01 (geometry) --- (continued)

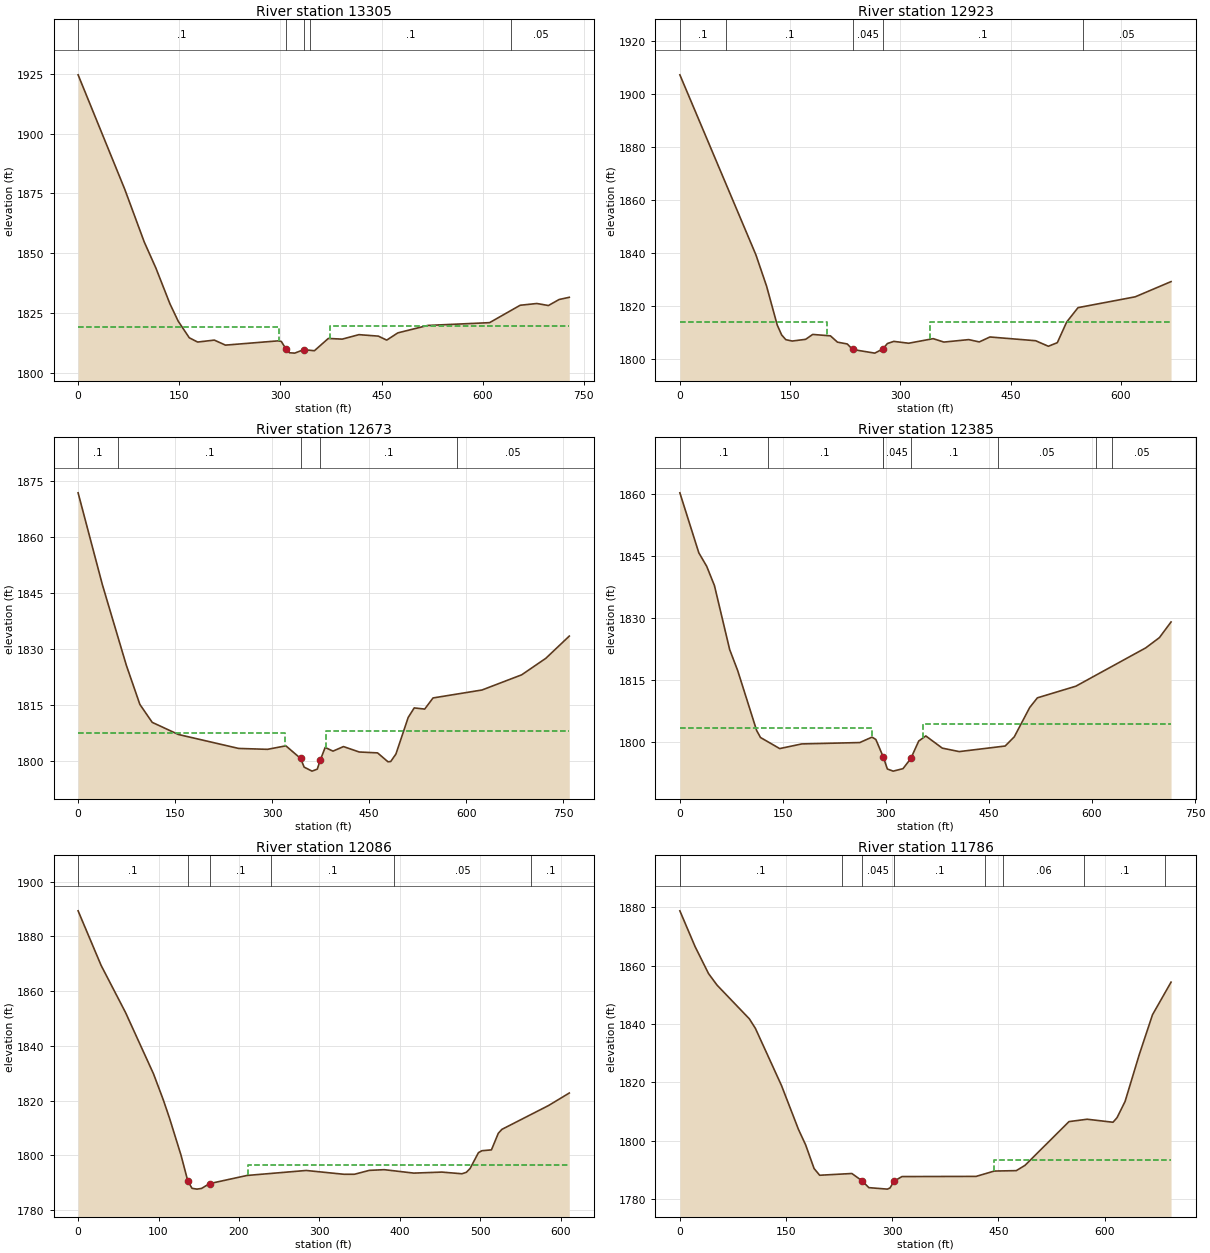
Type RM Length L Ch R = 1 ,13305   ,363.9,382.4,396.3
XS GIS Cut Line= 3
2471997.73272903578082.9905409862472089.85180441578116.519692245
     2472701.416      577964.125
#Sta/Elev= 30
       0 1924.57    69.2 1876.75      98  1854.8   115.4 1843.81   136.1 1828.96
   148.4 1821.67   164.9 1814.71   177.3 1812.94     202 1813.75   218.5 1811.65
   296.8 1813.44   301.4 1813.17     308 1810.13   313.3 1808.46   321.2 1808.31
   334.4 1809.75   350.4 1809.32     371 1814.44   391.6 1814.16   416.4 1816.03
   445.2 1815.41   457.6 1813.75   474.1 1816.77   518.3 1819.87   610.1 1821.04
   655.5 1828.31   680.2 1829.04   697.4  1828.2   713.2 1830.71   728.3 1831.63
#Mann= 5 ,-1 , 0
       0      .1       0     308    .045       0   334.4      .1       0
  343.44      .1       0  642.43     .05       0
#XS Ineff= 2 , 0
          298.22  1819.1  374.07         1819.49
Permanent Ineff=
       F       F
Bank Sta=308,334.4
XS Rating Curve= 0 ,0
Exp/Cntr=0.3,0.1

Type RM Length L Ch R = 1 ,12923   ,262.5,249.5,243.3
XS GIS Cut Line= 2
2471948.91059592578220.4790804892472503.08106547578594.397069225
#Sta/Elev= 30
       0 1907.09   103.5 1839.18     118 1827.38   132.5  1812.7   138.5 1808.97
   144.2 1807.18   152.9 1806.66   171.1  1807.3   180.8 1809.15   204.9 1808.62
   214.5 1806.24   227.8 1805.56   235.2 1803.47   265.3  1802.1   276.1 1803.66
   282.5 1805.73   291.2 1806.53   311.4 1805.83   344.8 1807.56   359.3 1806.27
   393.1  1807.2   407.5 1806.33     422 1808.19   484.2 1806.78   501.5 1804.69
   513.7 1806.04   526.4 1813.81   541.9 1819.26   619.7 1823.34   668.5 1829.08
#Mann= 5 ,-1 , 0
       0      .1       0   63.13      .1       0   235.2    .045       0
   276.1      .1       0  549.32     .05       0
#XS Ineff= 2 , 0
          200.57 1813.85  340.44         1813.75
Permanent Ineff=
       F       F
Bank Sta=235.2,276.1
XS Rating Curve= 0 ,0
Exp/Cntr=0.3,0.1

Type RM Length L Ch R = 1 ,12673   ,272.3,287.7,298.7
XS GIS Cut Line= 2
2471741.60159216578530.4483882452472491.43375771578651.855584653
#Sta/Elev= 30
       0 1871.74    37.6 1847.09    74.6 1825.53    95.5 1815.05   114.6 1810.23
   155.1 1806.98   248.3 1803.24   292.9    1803   321.3 1803.94   344.1 1800.56
   349.6 1798.23   361.8 1797.16   369.9  1797.7   374.5 1800.11   382.1 1803.51
   394.2 1802.52   410.4 1803.74   434.7 1802.29   463.1 1802.05   479.2 1799.67
   483.4 1799.73   491.5 1801.74   510.5 1811.55   519.8  1814.1     536 1813.79
   548.9 1816.77   624.6  1818.9     686 1822.97   723.3 1827.39   759.6 1833.35
#Mann= 5 ,-1 , 0
       0      .1       0   61.83      .1       0   344.1    .045       0
   374.5      .1       0  585.18     .05       0
#XS Ineff= 2 , 0
          319.93 1807.28  383.12         1807.78
Permanent Ineff=
       F       F
Bank Sta=344.1,374.5
XS Rating Curve= 0 ,0
Exp/Cntr=0.3,0.1

Type RM Length L Ch R = 1 ,12385   ,299.8,299.7,300.5
XS GIS Cut Line= 2
2471734.92605959578595.638640816     2472245.795      579095.886
#Sta/Elev= 30
       0 1860.37    27.6 1845.83      39 1842.59    50.3 1837.92    72.5  1822.4
    84.2  1817.3   111.7 1802.83   117.3 1801.11   145.3 1798.42   177.5 1799.55
   261.9 1799.88   279.7  1801.2   285.3 1800.62   296.3 1796.31     302 1793.48
   310.5 1792.96   324.8 1793.56   336.2 1796.02   347.7 1800.25     358 1801.48
     382 1798.53   406.7 1797.69   473.5 1799.04   486.8 1801.27   509.2 1808.36
   520.4 1810.71   576.4 1813.53   678.2 1822.82     698 1825.29     715 1829.09
#Mann= 8 ,-1 , 0
       0      .1       0  127.57      .1       0  294.96      .1       0
   296.3    .045       0   336.2      .1       0  462.36     .05       0
  605.85      .1       0  629.75     .05       0
#XS Ineff= 2 , 0
          279.02 1803.39  354.53         1804.34
Permanent Ineff=
       F       F
Bank Sta=296.3,336.2
XS Rating Curve= 0 ,0
Exp/Cntr=0.3,0.1

Type RM Length L Ch R = 1 ,12086   ,278.9,300,298.3
XS GIS Cut Line= 2
2471597.61152163578875.6963763272472065.20038041 579268.79611102
#Sta/Elev= 30
       0 1889.33    28.6 1869.42      59  1852.2    93.9 1829.74     106 1820.28
   113.8 1813.54     128 1800.11   136.5 1790.62   141.7 1788.01   147.8 1787.72
   153.5 1787.97   163.5 1789.73   210.1 1792.71   283.7 1794.53   330.7 1793.14
   343.8 1793.15   362.1 1794.57   380.7 1794.82   417.6 1793.57   452.5 1793.94
   477.4 1793.33   482.9 1793.86   487.5 1795.25   497.9 1801.03   502.2 1801.74
   514.1 1802.05   522.6  1808.1   527.1 1809.54   585.1 1818.24   610.9 1822.81
#Mann= 6 ,-1 , 0
       0      .1       0   136.5    .045       0   163.5      .1       0
  240.18      .1       0  392.37     .05       0  563.71      .1       0
#XS Ineff= 2 , 0
                          211.87         1796.56
Permanent Ineff=
       F       F
Bank Sta=136.5,163.5
XS Rating Curve= 0 ,0
Exp/Cntr=0.3,0.1

Type RM Length L Ch R = 1 ,11786   ,227,218.8,210.6
XS GIS Cut Line= 2
2471456.63111967579030.675735184     2471903.665      579561.585
#Sta/Elev= 30
       0 1878.74    21.5 1866.49    40.5 1857.25    52.6 1853.28    98.2 1841.75
   106.7 1838.51   143.6 1818.92   167.6 1803.88   177.7 1798.61   189.6 1790.52
   197.5  1788.2     243  1788.8   257.1 1786.36     267 1783.96   293.1 1783.45
   296.9 1783.84   302.6 1786.17   313.8 1787.75   418.6 1787.81   444.2 1789.64
   475.3 1789.78   487.7  1791.6   549.8 1806.57   575.5 1807.38     612 1806.35
   617.7 1807.93     629 1813.45   649.1 1829.53   667.8 1843.17     694 1854.32
#Mann= 9 ,-1 , 0
       0      .1       0     .67      .1       0  228.88      .1       0
   257.1    .045       0   302.6      .1       0  431.25     .02       0
  457.09     .06       0   571.2      .1       0  685.31      .1       0
#XS Ineff= 2 , 0
                          443.69         1793.55
Permanent Ineff=
       F       F
Bank Sta=257.1,302.6
XS Rating Curve= 0 ,0
Exp/Cntr=0.3,0.1

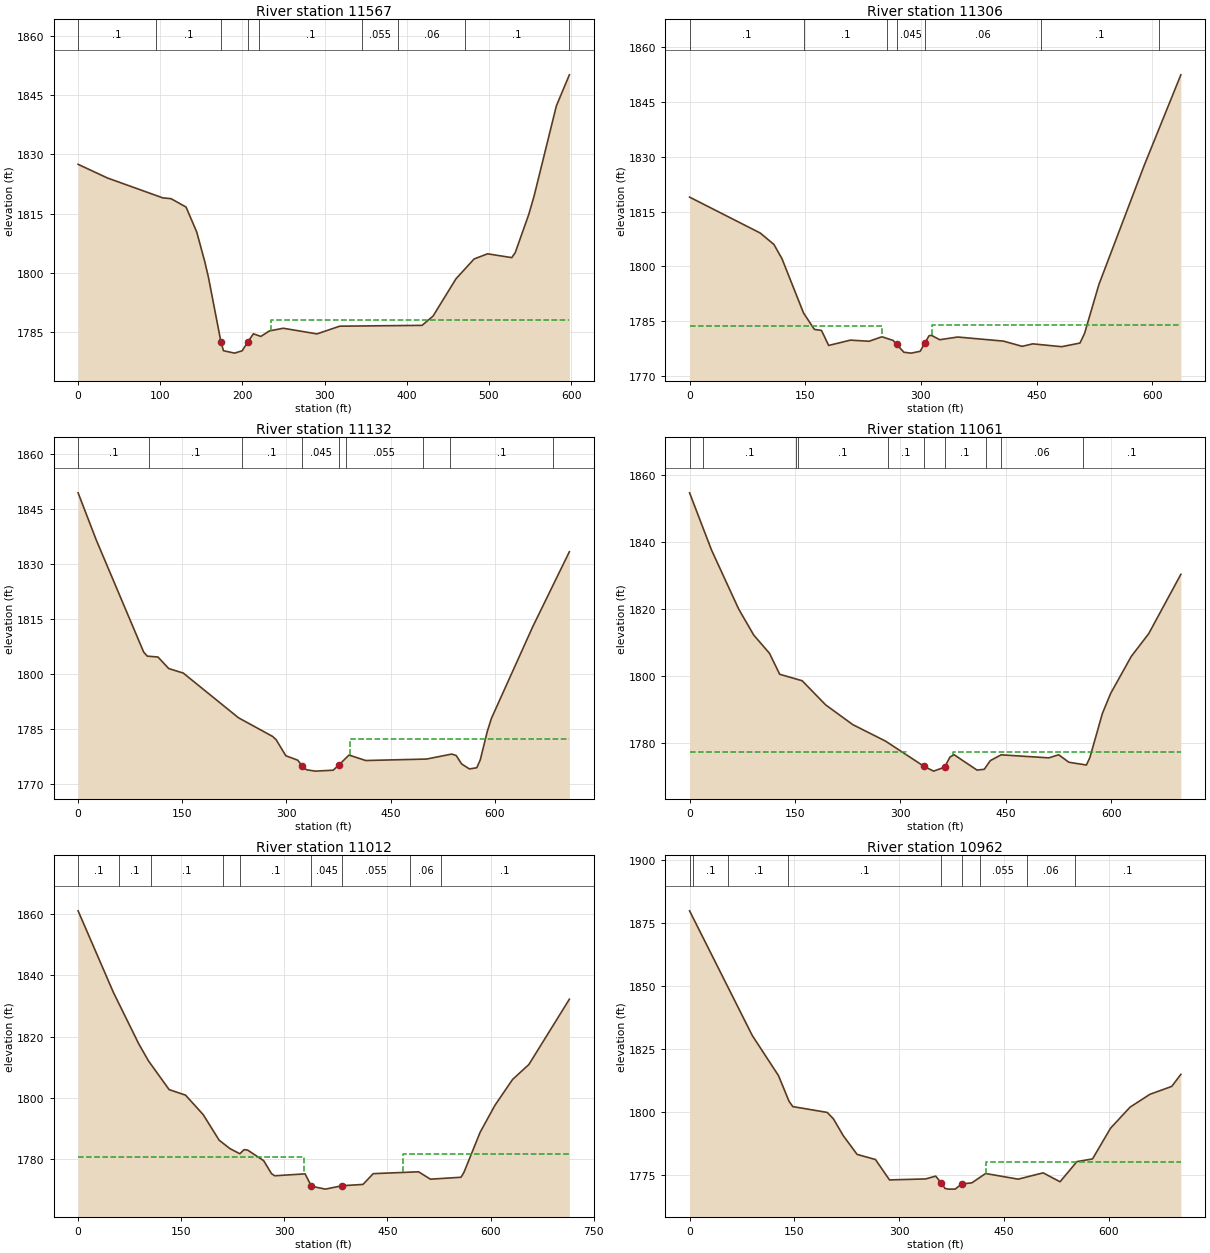
Type RM Length L Ch R = 1 ,11567   ,258.1,260.5,259.8
XS GIS Cut Line= 2
2471347.34222351579302.5230654692471872.63982694579588.141861551
#Sta/Elev= 30
       0 1827.45    35.7    1824   103.1 1818.97   113.1 1818.77   131.4 1816.65
   144.4 1810.33   154.1  1802.9   158.7 1798.83   173.8 1782.61   176.9 1780.34
   190.5 1779.73   199.7 1780.33   206.3 1782.47   213.3 1784.62   222.4 1783.95
   232.8 1785.34   249.7 1786.02   290.7 1784.59   318.4 1786.54   418.6 1786.75
   431.9 1789.07   459.9 1798.52   481.9 1803.52   498.3 1804.83   527.8 1803.87
     532 1805.13   548.4 1814.74   554.8  1819.3   582.1 1842.25   597.9 1850.07
#Mann= 9 ,-1 , 0
       0      .1       0   94.63      .1       0   173.8    .045       0
   206.3      .1       0  220.23      .1       0  345.82    .055       0
  389.49     .06       0  471.42      .1       0  597.02      .1       0
#XS Ineff= 2 , 0
                          235.18         1788.16
Permanent Ineff=
       F       F
Bank Sta=173.8,206.3
XS Rating Curve= 0 ,0
Exp/Cntr=0.3,0.1

Type RM Length L Ch R = 1 ,11306   ,174.7,174.7,178.6
XS GIS Cut Line= 2
2471151.59128441579476.2107689792471699.78589241579801.077753959
#Sta/Elev= 30
       0    1819    91.6 1809.17   109.4 1806.04   119.9 1802.11   147.8 1787.28
   161.9 1782.77   171.1  1782.5   180.4 1778.38   208.6 1779.84   232.8 1779.53
   249.5 1780.76   264.1 1779.75   268.7 1778.65     278 1776.52   287.3 1776.28
   299.1 1776.78     305 1778.95   310.5 1781.02   313.7 1781.15   324.5 1779.95
   347.7 1780.69   407.1 1779.57   431.4 1778.14   445.1 1778.82   482.6 1778.04
   506.4 1779.04   512.3 1781.68   530.9 1795.06   589.5 1827.59   637.2 1852.48
#Mann= 7 ,-1 , 0
       0      .1       0  149.05      .1       0  256.04      .1       0
   268.7    .045       0     305     .06       0  455.85      .1       0
  609.25      .1       0
#XS Ineff= 2 , 0
          249.34 1783.77  314.09         1784.03
Permanent Ineff=
       F       F
Bank Sta=268.7,305
XS Rating Curve= 0 ,0
Exp/Cntr=0.3,0.1

Type RM Length L Ch R = 1 ,11132   ,77,71.1,69.5
XS GIS Cut Line= 2
 2470997.5182991579519.344155376 2471546.2515982579965.757678563
#Sta/Elev= 30
       0 1849.45    26.1 1836.62    94.4 1806.06    99.6 1804.94     115  1804.7
   130.5 1801.56   151.4 1800.33   230.9 1788.15     280 1783.06   285.2 1782.16
   299.1 1777.79   316.2 1776.59   322.5 1775.06   328.9 1773.97   341.6  1773.6
   367.3 1773.85   375.9 1775.36   390.1 1777.98   414.1 1776.49   501.8 1776.89
     538 1778.25   544.4 1777.86   552.2 1775.57   563.4  1774.2     574 1774.52
   579.1 1776.67   589.1 1784.35   595.1 1787.96   654.5  1812.9   707.4  1833.4
#Mann= 9 ,-1 , 0
       0      .1       0  102.05      .1       0  236.03      .1       0
   322.5    .045       0   375.9      .1       0  385.44    .055       0
  496.03     .06       0  534.86      .1       0  684.27      .1       0
#XS Ineff= 2 , 0
                          391.02         1782.23
Permanent Ineff=
       F       F
Bank Sta=322.5,375.9
XS Rating Curve= 0 ,0
Exp/Cntr=0.5,0.3

Type RM Length L Ch R = 1 ,11061   ,48.5,48.4,49.2
XS GIS Cut Line= 3
  2470962.422386579586.8238055832471185.65404653579768.170000404
2471519.99825438580007.938100308
#Sta/Elev= 30
       0 1854.59    31.3 1837.53    69.9 1819.99    91.3 1812.26   113.8  1806.8
   128.2 1800.59   160.2 1798.66   193.6 1791.48   232.3 1785.59   278.7 1780.71
   333.3 1773.22   333.3 1773.21   347.2 1771.76   362.8 1772.94   370.6 1775.96
   376.3 1776.65     409 1772.07   419.3 1772.31   427.9 1774.89   443.3 1776.61
   511.1 1775.71   525.2 1776.63   539.7  1774.4   564.6 1773.58   569.5 1775.76
   587.4 1788.94   599.1 1794.88   628.5 1805.92   653.2 1812.65     699 1830.33
#Mann= 10 ,-1 , 0
       0      .1       0   19.52      .1       0  150.94      .1       0
  154.86      .1       0  282.35      .1       0   333.3    .045       0
   362.8      .1       0  421.25    .055       0  443.24     .06       0
  560.47      .1       0
#XS Ineff= 2 , 0
          307.87  1777.4  374.78          1777.5
Permanent Ineff=
       F       F
Bank Sta=333.3,362.8
XS Rating Curve= 0 ,0
Exp/Cntr(USF)=0,0
Exp/Cntr=0.5,0.3

Type RM Length L Ch R = 1 ,11012   ,49.5,50.7,52.9
XS GIS Cut Line= 3
2470932.89768947579624.5909741432471149.87987364579804.776130804
2471516.81480117580034.045243749
#Sta/Elev= 30
       0 1861.19    51.2 1834.53    88.2 1817.61   102.4 1812.02   132.4 1802.61
   156.3 1800.79   181.9 1794.43   205.2 1786.03   220.8 1783.28   235.3 1781.59
   241.5 1782.93   246.8 1782.76     270 1779.31   281.3 1775.07     286 1774.37
   330.2 1774.99   339.4 1770.94   359.7 1769.99   384.2 1771.11   414.4 1771.53
   429.3 1775.06   495.3 1775.67   512.5 1773.25   557.1 1773.88   561.3 1775.48
   584.9 1788.64   606.4 1797.45   632.1 1805.94   655.8 1810.83   714.7 1832.22
#Mann= 9 ,-1 , 0
       0      .1       0   59.19      .1       0  105.73      .1       0
  210.32      .1       0  235.89      .1       0   339.4    .045       0
   384.2    .055       0  483.42     .06       0  527.51      .1       0
#XS Ineff= 2 , 0
          328.83  1780.5   473.1         1781.55
Permanent Ineff=
       F       F
Bank Sta=339.4,384.2
XS Rating Curve= 0 ,0
Exp/Cntr=0.5,0.3

Type RM Length L Ch R = 1 ,10962   ,256.4,237.9,219.5
XS GIS Cut Line= 2
2470876.69230329579675.0276769272471457.58746447580071.895376564
#Sta/Elev= 30
       0 1879.91    89.7 1830.45   127.4 1814.45   142.4 1804.31   147.8 1802.18
   197.1 1799.87     206 1797.31   220.1 1790.63   239.9  1783.2   266.2 1781.17
   286.3 1773.07   338.1 1773.46   352.5 1774.58   360.1 1771.91   365.8 1769.68
   370.7 1769.41   380.3 1769.42   389.7 1771.44   404.3 1771.92   423.9 1775.61
   470.5 1773.37   506.3 1775.87   530.5 1772.33   554.7 1780.34     577  1781.4
   602.9 1793.63   630.8 1801.97   659.2 1807.06   690.4 1810.19   703.5 1814.98
#Mann= 9 ,-1 , 0
       0      .1       0    4.32      .1       0   55.57      .1       0
  141.35      .1       0   360.1    .045       0   389.7      .1       0
  415.42    .055       0  483.24     .06       0  552.45      .1       0
#XS Ineff= 2 , 0
                          424.67         1780.17
Permanent Ineff=
       F       F
Bank Sta=360.1,389.7
XS Rating Curve= 0 ,0
Exp/Cntr=0.3,0.1

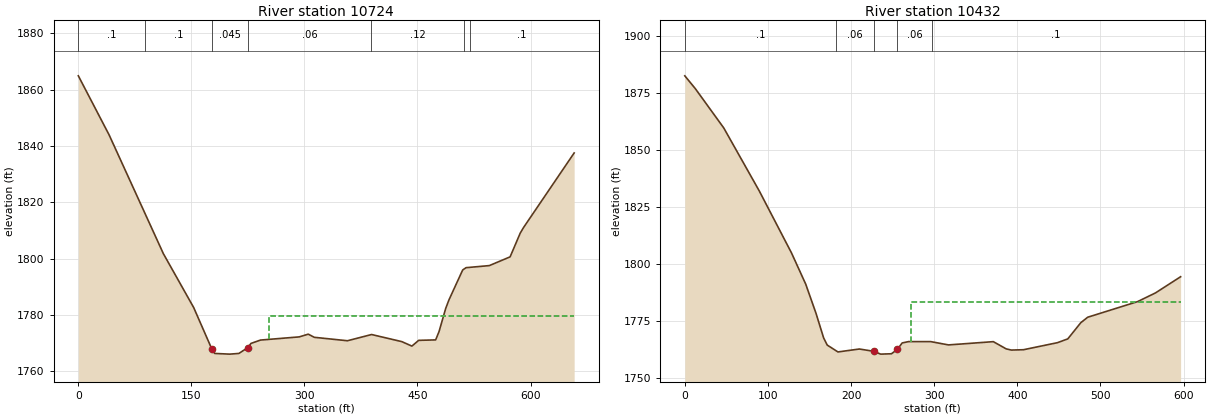
Type RM Length L Ch R = 1 ,10724   ,282.5,291.3,299.7
XS GIS Cut Line= 3
2470857.88146873580088.7538269392471250.04915722580073.889826939
     2471486.506      580194.535
#Sta/Elev= 30
       0 1864.94    40.9 1843.94   112.9 1801.77     153 1782.71     177 1768.03
     181 1766.38     201 1766.14     213 1766.38     225 1768.47     229 1769.93
   241.7 1771.13   293.1 1772.26   305.1 1773.23   313.1 1772.11   357.1 1770.89
   389.1  1773.1   429.2 1770.58   442.6 1768.99   451.6 1771.03   474.1 1771.19
   478.6 1774.13   487.5  1782.4   491.8 1785.41     510 1796.02   514.5 1796.83
   545.4 1797.57   572.9 1800.67   586.3 1809.06   590.8 1811.11   657.9 1837.56
#Mann= 7 ,-1 , 0
       0      .1       0   88.58      .1       0     177    .045       0
     225     .06       0   388.8     .12       0   511.1      .1       0
  519.17      .1       0
#XS Ineff= 2 , 0
                          252.47          1779.5
Permanent Ineff=
       F       F
Bank Sta=177,225
XS Rating Curve= 0 ,0
Exp/Cntr=0.3,0.1

Type RM Length L Ch R = 1 ,10432   ,361.5,346.5,335.4
XS GIS Cut Line= 2
2470819.05877649580278.2859382852471374.95871935580494.412550041
#Sta/Elev= 30
       0 1882.73    12.7 1877.09    46.9 1859.85    89.7 1832.16   128.4 1805.01
   145.5 1791.32   157.8 1778.59     167 1767.77   171.3 1764.64   184.2 1761.62
     210  1762.9   227.1 1761.91   235.7 1760.66   248.6 1760.82   255.6 1762.73
   261.5 1765.57   269.1 1766.15   295.8 1766.15   317.2  1764.7   371.1 1766.13
   386.5 1762.98   392.7 1762.44   407.4 1762.59   448.3 1765.69   460.7 1767.35
   476.3 1774.43   484.6 1776.84   544.7  1783.7   566.2 1787.52   596.4 1794.61
#Mann= 5 ,-1 , 0
       0      .1       0  181.63     .06       0   227.1    .045       0
   255.6     .06       0  296.85      .1       0
#XS Ineff= 2 , 0
                          272.63         1783.67
Permanent Ineff=
       F       F
Bank Sta=227.1,255.6
XS Rating Curve= 0 ,0
Exp/Cntr=0.3,0.1