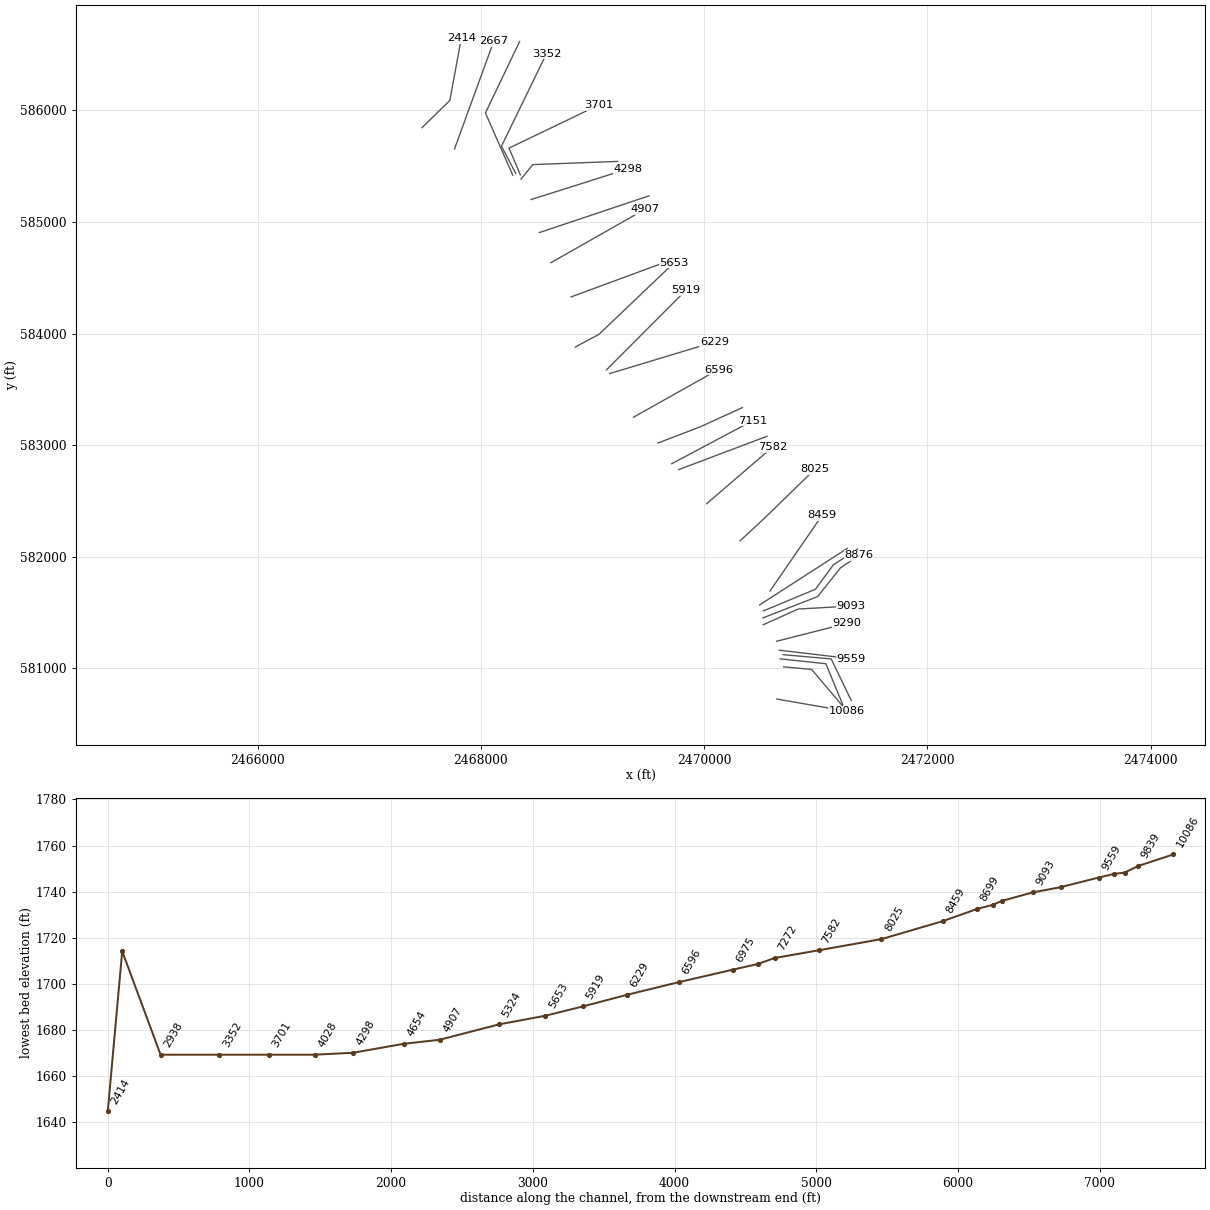
HEC-RAS study MILLERRN.prj: MILLERRN

--- MILLERRN.g01 (geometry) --- (continued)

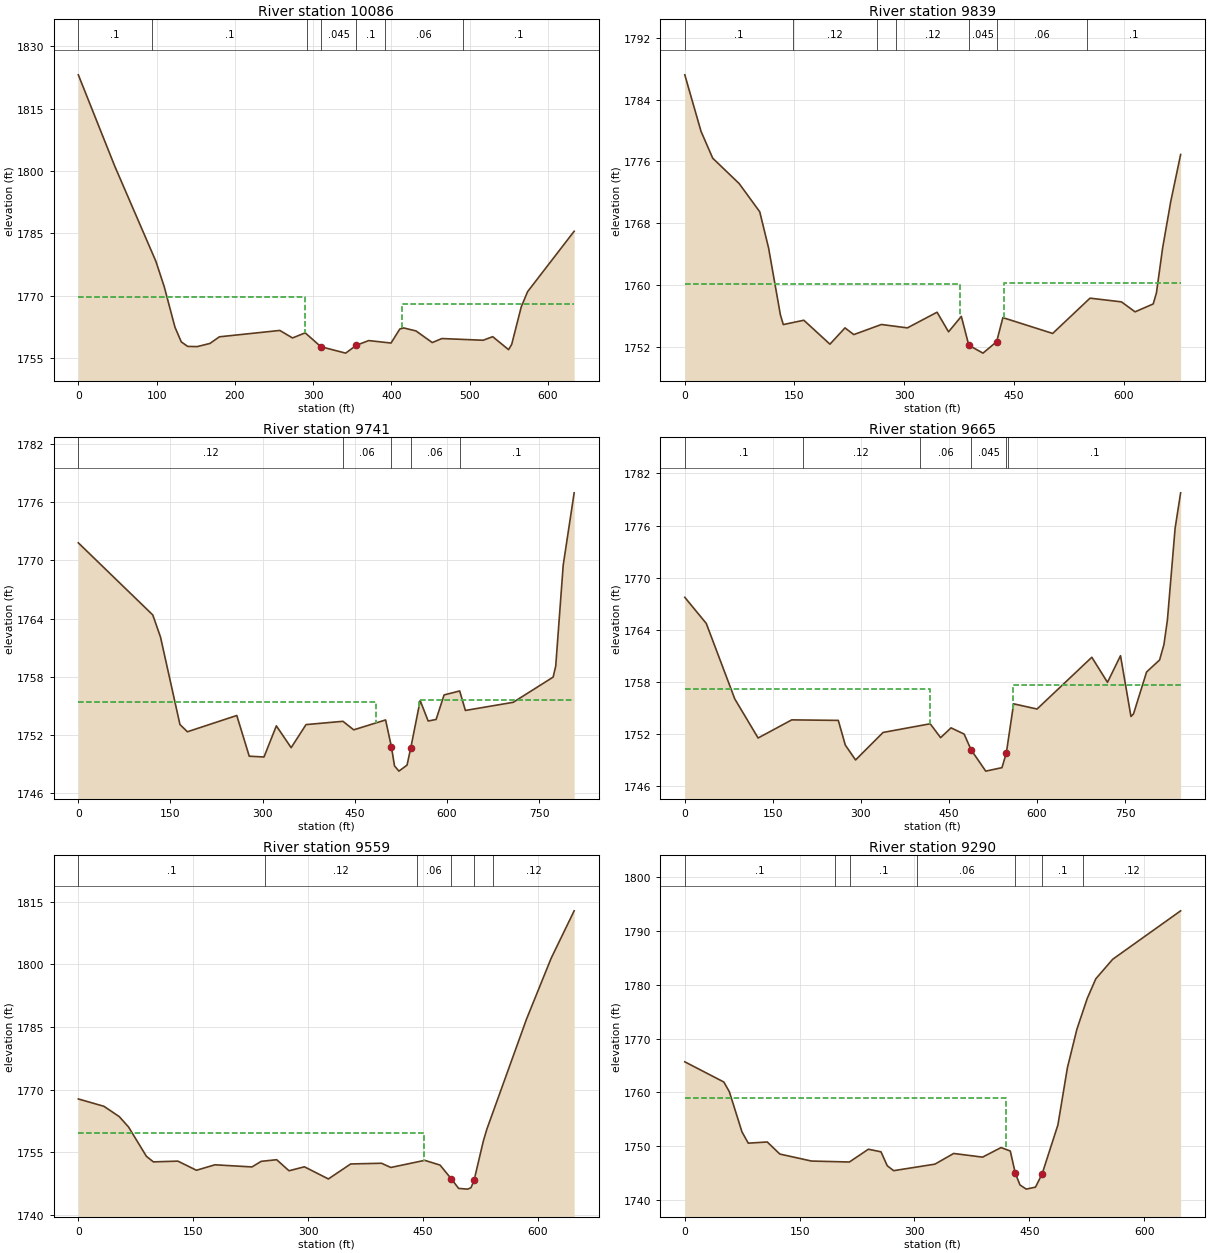
Type RM Length L Ch R = 1 ,10086   ,259.2,247.2,224.1
XS GIS Cut Line= 2
2470653.06611135580724.1057923272471277.37640033580615.841726857
#Sta/Elev= 30
       0 1823.12    46.4 1801.21    99.1 1778.25   109.8 1772.12   123.5 1762.38
   131.6 1758.85   139.7 1757.77   151.9 1757.72   168.2 1758.48   180.3 1760.08
   257.5 1761.61   273.7  1759.8   289.9 1761.03     310 1757.69   341.6 1756.15
   355.4 1758.05   371.1 1759.17   399.6 1758.58   410.8 1761.95   415.8 1762.21
   431.5 1761.49   452.3 1758.69   464.5 1759.66   517.3 1759.25   529.5 1760.11
   549.8 1756.99   553.8 1758.26     566 1767.29   574.1 1770.94   633.6 1785.48
#Mann= 7 ,-1 , 0
       0      .1       0   93.84      .1       0  292.48      .1       0
     310    .045       0   355.4      .1       0   391.8     .06       0
  491.13      .1       0
#XS Ineff= 2 , 0
          289.21 1769.71  413.86         1768.09
Permanent Ineff=
       F       F
Bank Sta=310,355.4
XS Rating Curve= 0 ,0
Exp/Cntr=0.3,0.1

Type RM Length L Ch R = 1 ,9839    ,102.2,97.5,89.4
XS GIS Cut Line= 3
2470712.68627042 581013.282142832470964.38453648580989.233719173
2471238.97368315580664.501937212
#Sta/Elev= 30
       0 1787.21    22.2 1779.89    38.2 1776.41    74.4 1773.12   102.5 1769.47
   114.6 1764.78   130.7 1756.14   134.7 1754.86   162.8 1755.42   198.5 1752.32
   219.1 1754.43   231.1 1753.56   268.9 1754.87   304.4 1754.43     345 1756.46
   360.7 1753.92   378.2 1755.92   388.4 1752.18   407.8 1751.16   426.5 1752.64
     435 1755.76   503.1 1753.71   554.2 1758.28   597.2  1757.8   615.8 1756.51
   640.6 1757.53     645 1758.95   653.5 1764.79   664.5 1770.75   678.1 1776.89
#Mann= 7 ,-1 , 0
       0      .1       0  147.36     .12       0   262.3      .1       0
  289.17     .12       0   388.4    .045       0   426.5     .06       0
  550.67      .1       0
#XS Ineff= 2 , 0
          377.02  1760.1  436.58         1760.26
Permanent Ineff=
       F       F
Bank Sta=388.4,426.5
XS Rating Curve= 0 ,0
Exp/Cntr=0.5,0.3

Type RM Length L Ch R = 1 ,9741    ,95.8,75.9,75.6
XS GIS Cut Line= 3
2470682.26433993581084.5943399272471091.40136493 581040.83619353
2471242.32017243580675.263103693
#Sta/Elev= 30
       0 1771.82   121.2 1764.38   133.8 1762.09   165.4 1753.08   177.5 1752.33
   257.9 1754.01   278.2 1749.81   302.2 1749.73   322.3 1752.94   346.4 1750.69
   370.6 1753.07   430.7 1753.41   448.2 1752.53   500.1 1753.55   509.6 1750.78
   514.6 1748.81   521.8 1748.27     535 1748.89   541.1 1750.68   556.4 1755.55
   569.4 1753.44   582.3  1753.6   595.3 1756.13   620.7 1756.54     630 1754.53
   707.8 1755.37   772.8 1757.97     777 1759.11   789.2 1769.53     807 1776.98
#Mann= 5 ,-1 , 0
       0     .12       0   430.7     .06       0   509.6    .045       0
   541.1     .06       0   620.7      .1       0
#XS Ineff= 2 , 0
          485.09  1755.4  554.39          1755.6
Permanent Ineff=
       F       F
Bank Sta=509.6,541.1
XS Rating Curve= 0 ,0
Exp/Cntr=0.5,0.3

Type RM Length L Ch R = 1 ,9665    ,63.1,106,129.9
XS GIS Cut Line= 3
2470710.31513201581121.9679742132471138.88200314581083.877764217
2471319.10912194 580710.66009003
#Sta/Elev= 30
       0 1767.72    36.6 1764.71    85.2    1756   124.9  1751.5   182.2 1753.59
   261.5 1753.53   273.5 1750.68   290.9 1748.97   337.8 1752.14   418.1 1753.14
   435.8 1751.54   453.6 1752.67   475.9 1751.95   487.8 1750.13   512.7 1747.68
   540.3 1748.08   547.7 1749.74   560.2 1755.44   600.1 1754.84   693.4 1760.81
   720.1 1757.92   742.3 1760.99   760.1 1753.98   764.5 1754.29   786.7 1759.11
   808.9  1760.5   816.3 1762.28   822.2 1765.11   835.3 1775.68   844.7 1779.77
#Mann= 6 ,-1 , 0
       0      .1       0  200.84     .12       0  399.99     .06       0
   487.8    .045       0   547.7     .06       0  550.82      .1       0
#XS Ineff= 2 , 0
          418.42 1757.12  558.77         1757.62
Permanent Ineff=
       F       F
Bank Sta=487.8,547.7
XS Rating Curve= 0 ,0
Exp/Cntr=0.5,0.3

Type RM Length L Ch R = 1 ,9559    ,259.5,269.4,274.3
XS GIS Cut Line= 2
2470673.58070916581162.2318546482471316.47425757581086.149777914
#Sta/Elev= 30
       0 1767.74    33.4 1765.98    53.5  1763.5    65.6 1761.01    88.9 1753.99
      98 1752.66     130 1752.84   154.2 1750.65   178.4 1751.96   226.7 1751.45
   238.8 1752.79     259 1753.18   275.1 1750.53   295.2 1751.48   326.5 1748.57
   355.6 1752.16   395.9 1752.33     408 1751.32   452.3 1753.03   472.3 1751.89
   486.7 1748.66   496.6  1746.3   508.3 1746.13   512.7 1746.47   516.7 1748.22
   528.8 1757.64   533.5 1760.55   585.2 1786.87   617.4 1801.47   647.4 1812.82
#Mann= 6 ,-1 , 0
       0      .1       0  243.24     .12       0  442.06     .06       0
   486.7    .045       0   516.7     .06       0  541.47     .12       0
#XS Ineff= 2 , 0
           450.7 1759.55
Permanent Ineff=
       F       F
Bank Sta=486.7,516.7
XS Rating Curve= 0 ,0
Exp/Cntr(USF)=0,0
Exp/Cntr=0.3,0.1

Type RM Length L Ch R = 1 ,9290    ,199.3,197.4,191.4
XS GIS Cut Line= 2
 2470650.3895809581242.3129691432471278.03087478581402.074623565
#Sta/Elev= 30
       0 1765.66      51  1761.9    58.2 1760.09    74.7 1752.61    82.9 1750.51
   107.7 1750.73   124.2 1748.48   165.5 1747.18     215    1747   239.8 1749.38
   256.3  1748.9   264.5  1746.3   272.8 1745.39   326.7  1746.6   351.2 1748.59
     389 1747.91   413.1 1749.69   425.2 1749.05   431.8 1744.87   437.9 1742.72
   446.1 1741.95   458.1 1742.32   466.8  1744.8   487.4 1753.91   499.8 1764.55
   512.2 1771.73   525.7 1777.46   536.9 1781.12   558.9 1784.75   647.7 1793.78
#Mann= 7 ,-1 , 0
       0      .1       0  195.63     .12       0  215.28      .1       0
  303.92     .06       0   431.8    .045       0   466.8      .1       0
   520.5     .12       0
#XS Ineff= 2 , 0
          419.22 1758.83
Permanent Ineff=
       F       F
Bank Sta=431.8,466.8
XS Rating Curve= 0 ,0
Exp/Cntr=0.3,0.1

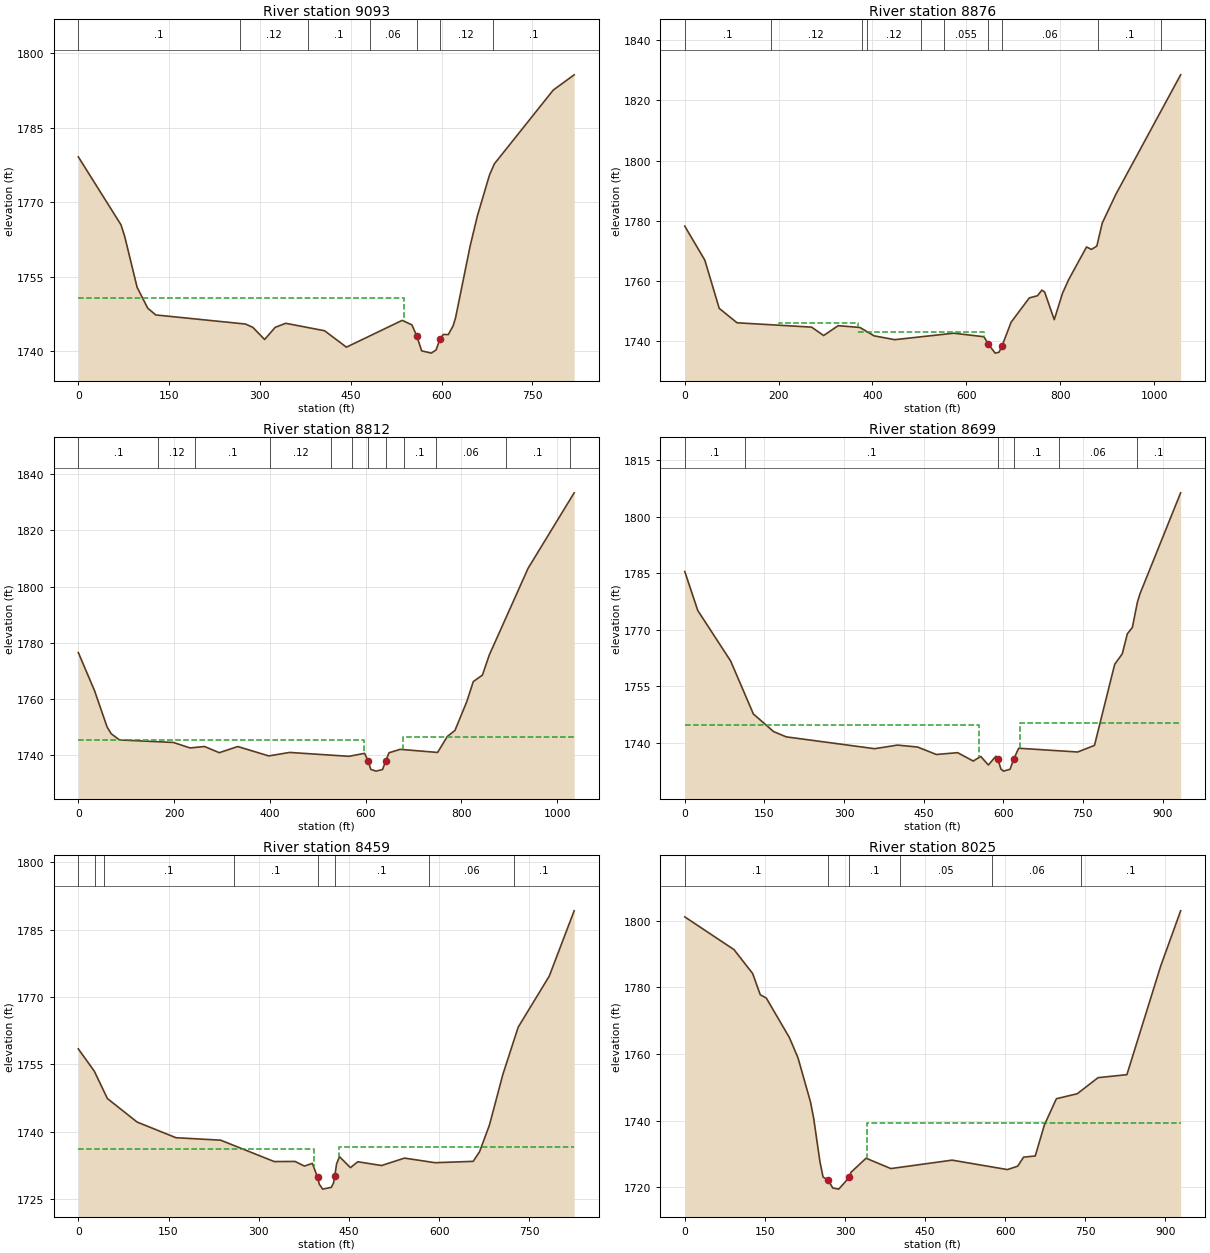
Type RM Length L Ch R = 1 ,9093    ,200.8,216.1,230.7
XS GIS Cut Line= 3
2470530.26816463581390.1081428582470842.33540136581530.776503401
2471318.33134422581558.044468027
#Sta/Elev= 30
       0 1779.12    70.5 1765.46    76.6 1763.13    97.1  1752.9   114.6 1748.71
   127.8 1747.34   276.2 1745.51   288.3 1744.84   307.7  1742.4   325.2 1744.84
   342.6 1745.66   406.8 1744.16   442.9 1740.86     535 1746.25   551.1 1745.34
   559.4 1743.03   567.1 1740.12   583.1 1739.66   591.1 1740.32   597.6 1742.58
   603.1 1743.42   611.2 1743.38   619.2 1745.16   623.2 1746.77   647.2 1761.16
   659.2 1767.25   679.3  1775.5   687.3 1777.72   784.6 1792.56   819.1 1795.62
#Mann= 7 ,-1 , 0
       0      .1       0  266.53     .12       0  379.29      .1       0
  481.02     .06       0   559.4    .045       0   597.6     .12       0
  684.46      .1       0
#XS Ineff= 2 , 0
           538.6 1750.67
Permanent Ineff=
       F       F
Bank Sta=559.4,597.6
XS Rating Curve= 0 ,0
Exp/Cntr=0.5,0.3

Type RM Length L Ch R = 1 ,8876    ,62.9,64.6,67.2
XS GIS Cut Line= 4
2470526.94919265581451.6070888172471017.98435304581642.815844066
2471222.13792561581900.2268703492471390.08571184582010.958918693
#Sta/Elev= 30
       0 1778.21    42.7 1766.93    73.4  1750.9   111.4 1746.11   270.2 1744.67
   295.9 1741.88   326.8 1745.15   373.2 1744.56   403.3 1741.78   447.3  1740.5
   573.2 1742.65   637.6 1741.47   647.1 1738.97   661.4 1736.03   669.8 1736.34
   676.2 1738.47   695.4 1746.29   734.2 1754.38   751.7  1755.1     761 1756.98
     767  1756.3   787.4 1747.14     805 1755.93     818 1760.42   856.2 1771.31
   866.5 1770.49   878.1 1771.59   889.6 1779.22   918.5 1788.75  1056.7  1828.5
#Mann= 10 ,-1 , 0
       0      .1       0  182.78     .12       0  377.24      .1       0
  388.46     .12       0  503.71     .06       0  552.76    .055       0
   647.1    .045       0   676.2     .06       0  880.33      .1       0
 1015.27     .12       0
#XS Ineff= 3 ,-1
     200     369    1746     369     6371743.151  688.44     700  1742.3
Permanent Ineff=
       F       F       F
Bank Sta=647.1,676.2
XS Rating Curve= 0 ,0
Exp/Cntr=0.5,0.3

Type RM Length L Ch R = 1 ,8812    ,120.1,112.6,102.9
XS GIS Cut Line= 4
2470531.31248272581514.2934604092470997.62228027581708.106013606
2471158.14131456  581926.9182162     2471375.316      582068.268
#Sta/Elev= 30
       0  1776.5      34 1762.88      60 1750.04    68.7 1747.61      86 1745.41
   198.6 1744.51   233.3 1742.56   263.6 1743.07   294.3 1740.87   332.9 1743.06
   397.8 1739.72   441.2 1740.96     565 1739.58   597.7 1740.64   605.1 1738.04
   610.8 1734.94   621.8 1734.31   635.4 1734.89   642.1 1738.01   648.9 1740.85
   672.1 1742.06   750.3 1740.96   770.6 1746.64   786.6  1748.8   811.5 1759.16
   824.8 1766.16   843.9 1768.48   858.2 1775.61   939.3 1806.48  1035.5 1833.33
#Mann= 12 ,-1 , 0
       0      .1       0  166.87     .12       0     243      .1       0
  400.53     .12       0  528.12    .055       0  570.99     .06       0
   605.1    .045       0   642.1     .06       0  680.88      .1       0
  746.48     .06       0  892.21      .1       0 1026.42     .12       0
#XS Ineff= 2 , 0
          596.68 1745.55  678.49         1746.56
Permanent Ineff=
       F       F
Bank Sta=605.1,642.1
XS Rating Curve= 0 ,0
Exp/Cntr=0.5,0.3

Type RM Length L Ch R = 1 ,8699    ,231.5,240.1,246.5
XS GIS Cut Line= 2
2470498.19659713581568.2868442942471283.09558125 582074.49510053
#Sta/Elev= 30
       0 1785.48    24.5 1775.13    86.3 1761.75   129.2 1747.67   167.2    1743
     191 1741.59   357.6 1738.45   400.5  1739.4   438.5 1738.89   473.9 1736.91
     514 1737.39   543.3 1735.17   557.5 1736.39   571.8 1734.12   586.1 1736.46
   589.7 1735.65   595.6 1733.02   600.4 1732.49   612.8 1732.99   619.4 1735.61
   628.9 1738.57   740.1 1737.57   771.7 1739.32   809.8 1760.85   824.1 1763.65
   833.6 1768.94   843.1 1770.66   852.6 1777.36   857.4 1779.56     934 1806.39
#Mann= 6 ,-1 , 0
       0      .1       0  112.91      .1       0   589.7    .045       0
   619.4      .1       0  704.92     .06       0  851.68      .1       0
#XS Ineff= 2 , 0
          555.05 1744.64  631.58         1745.32
Permanent Ineff=
       F       F
Bank Sta=589.7,619.4
XS Rating Curve= 0 ,0
Exp/Cntr=0.3,0.1

Type RM Length L Ch R = 1 ,8459    ,435.9,434.6,427
XS GIS Cut Line= 2
     2470591.347       581693.08     2471058.588      582372.485
#Sta/Elev= 30
       0 1758.44    26.5  1753.5    48.4 1747.39    97.8 1742.16   162.4 1738.68
   236.7 1738.13   325.9 1733.37   360.4  1733.4     376 1732.37   389.2 1732.97
   397.8 1729.91   400.7 1728.34   406.4 1727.24   420.8 1727.64   424.5 1728.65
   426.6 1730.26   429.5 1732.85   434.3 1734.47   452.5 1732.02   464.8 1733.33
   504.2 1732.49   542.5 1734.14   593.4 1733.12   656.7 1733.42   667.3 1735.57
   683.7 1741.49   706.1 1752.78   731.5 1763.27   783.3 1774.66   824.6 1789.16
#Mann= 8 ,-1 , 0
       0      .1       0   27.82      .1       0   42.43      .1       0
  258.89      .1       0   397.8    .045       0   426.6      .1       0
  583.57     .06       0  724.82      .1       0
#XS Ineff= 2 , 0
          392.18 1736.21  433.69         1736.52
Permanent Ineff=
       F       F
Bank Sta=397.8,426.6
XS Rating Curve= 0 ,0
Exp/Cntr=0.3,0.1

Type RM Length L Ch R = 1 ,8025    ,442.2,442.2,439.5
XS GIS Cut Line= 3
2470323.14154014582142.859590475     2470531.032      582335.571
 2470993.5768068582784.944857141
#Sta/Elev= 30
       0 1801.15    92.2 1791.32   127.1 1784.14   141.3 1777.78   152.6 1776.79
   195.8 1764.94   211.9 1758.88   235.4 1745.58   241.3 1740.72   253.1 1727.62
   258.9 1723.06   268.6 1722.12   277.1 1719.77   288.2 1719.43   308.2    1723
   311.2 1724.49   339.4 1728.71   385.8  1725.6   500.6 1728.13     604  1725.3
   623.3 1726.31   634.4 1729.03   656.2 1729.38   673.2 1738.65   695.8 1746.57
   734.8 1748.06   773.8 1752.89   827.8 1753.79     891 1786.35   928.4 1802.97
#Mann= 6 ,-1 , 0
       0      .1       0   268.6    .045       0   308.2      .1       0
  402.83     .05       0  575.62     .06       0  742.13      .1       0
#XS Ineff= 2 , 0
                          341.23         1739.35
Permanent Ineff=
       F       F
Bank Sta=268.6,308.2
XS Rating Curve= 0 ,0
Exp/Cntr=0.3,0.1

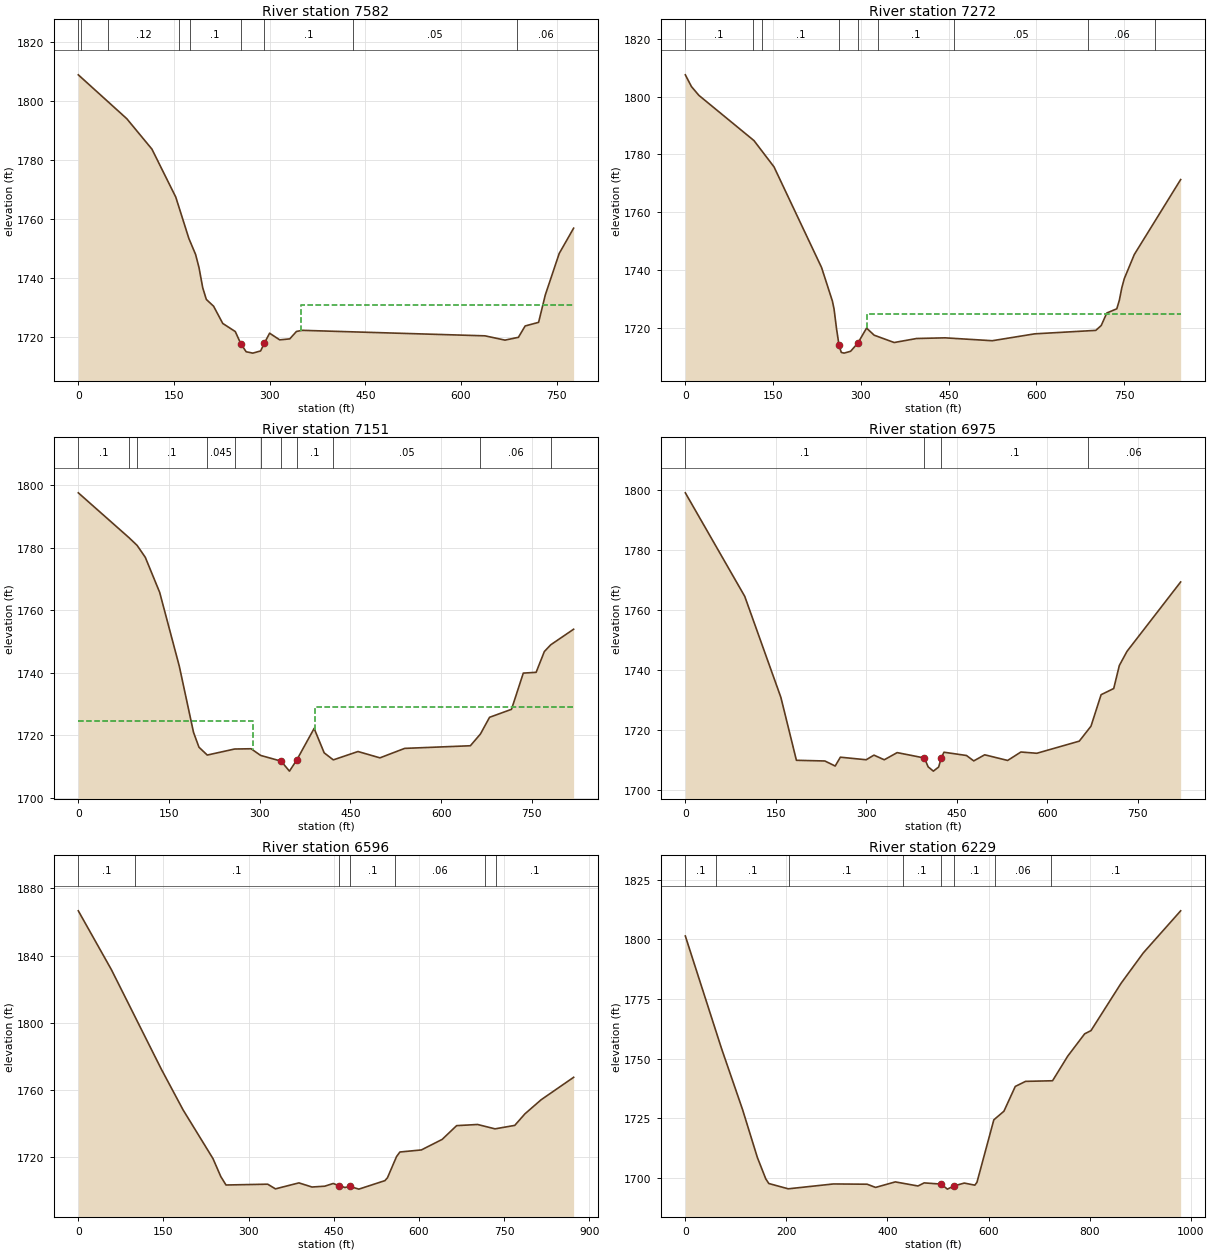
Type RM Length L Ch R = 1 ,7582    ,314.1,310.5,299.2
XS GIS Cut Line= 2
2470023.19233877582475.382590475 2470612.3804898582981.092496598
#Sta/Elev= 30
       0 1808.74    75.9 1793.92   115.4 1783.61   152.8 1767.38   173.4 1753.34
   183.9 1747.96   189.2 1743.56   195.1 1736.67   200.7 1732.76   212.1 1730.45
   226.5 1724.62   246.1 1721.89   254.6 1717.84   263.1 1715.06   273.5 1714.59
   285.8 1715.33   291.5 1717.88   299.9 1721.34   315.7 1719.08   331.5 1719.41
     342 1721.92   351.1  1722.3   637.6 1720.44   668.9 1718.99     690 1719.94
   700.5 1723.78   721.6    1725   732.1 1734.27   753.9  1748.3   776.5 1756.86
#Mann= 9 ,-1 , 0
       0     .12       0    4.21      .1       0   46.17     .12       0
  158.24      .1       0   174.5      .1       0   254.6    .045       0
   291.5      .1       0  431.14     .05       0  687.79     .06       0
#XS Ineff= 2 , 0
                          349.73         1730.79
Permanent Ineff=
       F       F
Bank Sta=254.6,291.5
XS Rating Curve= 0 ,0
Exp/Cntr=0.3,0.1

Type RM Length L Ch R = 1 ,7272    ,117.7,120.8,122.7
XS GIS Cut Line= 2
2469772.99781134582780.7166373392470564.81373469 583079.76141421
#Sta/Elev= 30
       0 1807.51    10.4 1803.46    23.2  1800.4   117.3 1784.76   151.5 1775.68
   232.8 1740.85   251.3 1729.25   254.1 1726.55   258.4 1719.63   262.7 1713.91
   266.5 1711.49   271.2 1711.24   282.4 1711.88   294.7 1714.68   309.7  1719.9
   322.7 1717.44   356.9 1714.91   395.2  1716.3   443.8 1716.53   524.5 1715.53
     597 1717.91   701.4 1719.11   710.7  1720.8   720.2 1725.12   737.3 1726.58
   741.6 1729.49   745.9 1733.89   750.1 1737.01   767.2 1745.35   846.4 1771.28
#Mann= 9 ,-1 , 0
       0      .1       0  115.26     .12       0  130.63      .1       0
   262.7    .045       0   294.7      .1       0  328.58      .1       0
  458.96     .05       0  688.09     .06       0  802.65      .1       0
#XS Ineff= 2 , 0
                          310.43         1724.61
Permanent Ineff=
       F       F
Bank Sta=262.7,294.7
XS Rating Curve= 0 ,0
Exp/Cntr=0.3,0.1

Type RM Length L Ch R = 1 ,7151    ,178.2,176.5,173.8
XS GIS Cut Line= 2
2469710.54697552582833.2267626952470433.41718433583217.952434687
#Sta/Elev= 30
       0 1797.46    83.6 1783.18    97.2 1780.69   110.8 1776.86   134.5  1765.7
     167  1742.1   190.5 1720.99   199.5 1716.25   213.2 1713.75   258.5 1715.68
   285.7 1715.76   301.5 1713.63   335.21711.813   349.1 1708.62   361.1 1712.15
   389.9 1722.25   406.5 1714.46   421.6 1712.21   462.4 1714.88   498.7 1712.86
   539.6 1715.88   648.2 1716.72   664.8 1720.46   679.9  1725.8   716.2 1728.35
   735.7 1739.91   756.9 1740.16   770.5 1746.79   781.1 1748.95   818.9 1753.92
#Mann= 11 ,-1 , 0
       0      .1       0    83.6     .12       0    97.2      .1       0
   213.2    .045       0   258.5      .1       0   301.5      .1       0
   335.2    .045       0   361.1      .1       0   421.6     .05       0
   664.8     .06       0   781.1      .1       0
#XS Ineff= 2 , 0
          288.34 1724.49  391.23         1729.12
Permanent Ineff=
       F       F
Bank Sta=335.2,361.1
XS Rating Curve= 0 ,0
Exp/Cntr(USF)=0,0
Exp/Cntr=0.3,0.1

Type RM Length L Ch R = 1 ,6975    ,374.7,378.9,379.5
XS GIS Cut Line= 3
     2469586.766      583018.699     2469971.874      583166.586
     2470343.635      583336.773
#Sta/Elev= 30
       0  1798.9    98.5 1764.41   158.5 1730.71   184.2 1709.78   231.4 1709.55
   248.5 1707.87   257.1 1710.81   299.9 1709.96   312.8  1711.5   329.9 1709.95
   351.3 1712.34   396.4 1710.55   402.7 1707.59   411.3 1706.17   420.1 1707.54
   424.5 1710.62   428.9 1712.47   466.2 1711.38   478.3 1709.58   496.4 1711.61
   534.5 1709.73   556.5 1712.54   582.9 1712.12   653.3 1716.16   672.7 1721.14
   689.5 1731.64   710.4 1733.69   719.7 1741.36   732.4 1746.07   821.4  1769.2
#Mann= 4 ,-1 , 0
       0      .1       0   396.4    .045       0   424.5      .1       0
  667.03     .06       0
Bank Sta=396.4,424.5
XS Rating Curve= 0 ,0
Exp/Cntr=0.3,0.1

Type RM Length L Ch R = 1 ,6596    ,367.7,366.5,360.7
XS GIS Cut Line= 2
2469367.93441878583250.3106800022470128.55510694583677.690290612
#Sta/Elev= 30
       0 1866.69    58.3 1831.62   146.4  1772.2   184.6 1748.01   237.2 1719.01
     251 1708.29   260.2 1703.25   333.6 1703.73   347.3 1700.95   388.6 1704.51
   411.6 1702.05     434 1702.53     449 1704.15   458.5 1702.92   469.6 1701.78
   478.4 1702.39   494.2 1700.79   540.1 1705.85   544.6 1707.58   560.6  1720.2
   566.5 1722.92   604.3 1724.15     641 1730.44   666.4 1738.64   703.4 1739.32
     734 1736.72   768.8 1738.78   786.8 1745.69   815.3 1754.07   872.5 1767.44
#Mann= 7 ,-1 , 0
       0      .1       0  100.15      .1       0   458.5    .045       0
   478.4      .1       0  558.71     .06       0  716.57      .1       0
  735.03      .1       0
Bank Sta=458.5,478.4
XS Rating Curve= 0 ,0
Exp/Cntr=0.3,0.1

Type RM Length L Ch R = 1 ,6229    ,298.2,309.7,318.6
XS GIS Cut Line= 2
2469154.33101134583641.3279854712470092.61794857583925.048179592
#Sta/Elev= 30
       0 1801.43    71.5 1754.32   113.3 1728.61   142.5 1708.59   159.2 1699.59
   165.2 1697.64   203.7 1695.42     293 1697.46   359.8 1697.35   376.5 1696.01
   415.5 1698.32   460.4 1696.61   472.6 1697.91   506.1 1697.39   518.6 1695.29
   531.4 1696.61     552 1697.83   572.9 1696.95   577.1 1698.14   610.5 1724.35
   630.5 1727.96   652.9 1738.34   673.2 1740.47   726.7 1740.73   756.8 1751.07
   790.2  1760.4   802.8 1761.76   862.2 1781.57   906.4 1794.37   980.2 1811.98
#Mann= 8 ,-1 , 0
       0      .1       0    59.9      .1       0  205.85      .1       0
  431.15      .1       0   506.1    .045       0   531.4      .1       0
  612.56     .06       0  723.09      .1       0
Bank Sta=506.1,531.4
XS Rating Curve= 0 ,0
Exp/Cntr=0.3,0.1

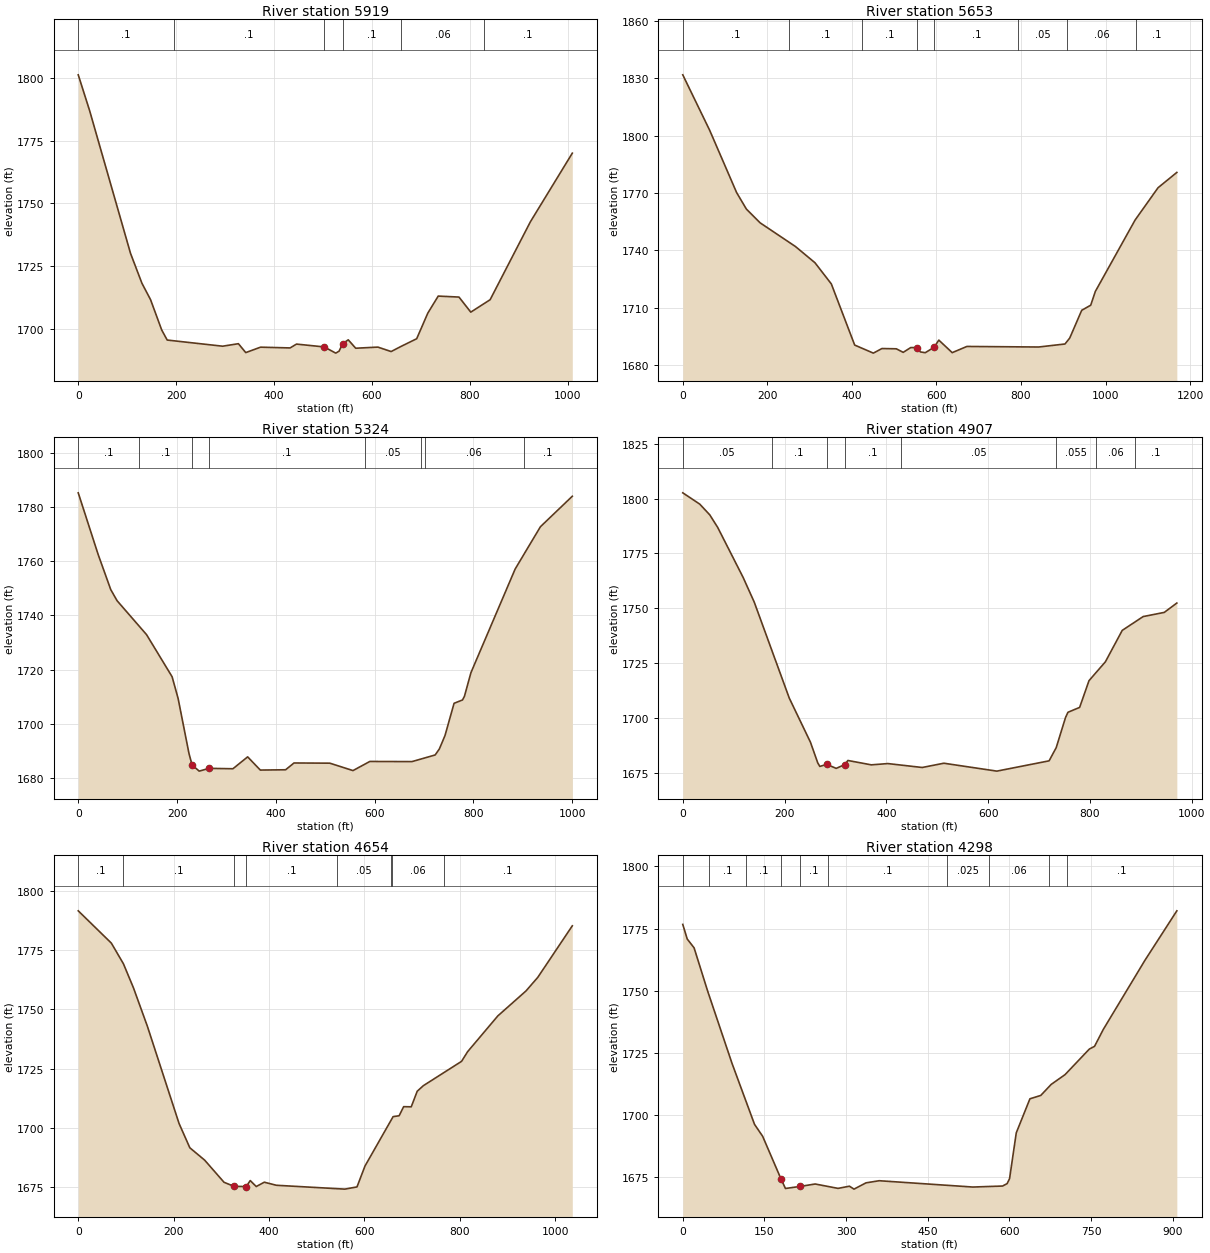
Type RM Length L Ch R = 1 ,5919    ,266.7,266.8,264.8
XS GIS Cut Line= 2
2469126.37223104583675.2542310412469839.27991921 584389.74775443
#Sta/Elev= 30
       0 1801.18    23.2 1786.94   106.8 1730.04   130.1 1718.13   147.8 1711.55
   170.4 1699.55   181.7 1695.49     295 1693.04   327.2 1694.04   342.2 1690.49
   372.4 1692.65   432.8 1692.35   445.9 1693.88   502.4 1692.75   526.1 1690.28
   532.9 1691.07   540.2 1694.07   551.6 1695.58   566.8 1692.23   612.1 1692.68
   639.2 1690.91     659 1692.91   691.4 1696.02   714.1 1706.22   735.4 1713.01
   777.8 1712.62   801.9 1706.61   841.4 1711.56   923.6 1742.59  1009.3 1769.96
#Mann= 6 ,-1 , 0
       0      .1       0  194.84      .1       0   502.4    .045       0
   540.2      .1       0     659     .06       0  829.08      .1       0
Bank Sta=502.4,540.2
XS Rating Curve= 0 ,0
Exp/Cntr=0.3,0.1

Type RM Length L Ch R = 1 ,5653    ,334,328.6,317.3
XS GIS Cut Line= 3
2468846.52128664583879.4919074992469058.40922498583992.935885808
2469730.18608336584633.562647505
#Sta/Elev= 30
       0  1831.8    63.8 1802.71   127.3 1770.24   150.4 1761.59   182.9 1754.39
   266.4 1742.01   312.7  1733.5   351.4 1722.41   406.6 1690.44   450.8 1686.22
   471.1 1688.62   505.1 1688.48   521.4 1686.63   539.3 1689.14   553.2 1689.11
     562 1686.85   573.6 1686.45   594.6  1689.3   605.6 1693.03   637.3 1686.47
     672 1689.71   841.8 1689.42   904.1    1691   915.3 1694.12   943.6 1708.62
   964.9 1711.29   975.9 1718.52  1069.9 1755.85  1124.2 1772.75  1168.6 1780.74
#Mann= 8 ,-1 , 0
       0      .1       0  250.52      .1       0  425.09      .1       0
   553.2    .045       0   594.6      .1       0  794.06     .05       0
  908.36     .06       0 1072.81      .1       0
Bank Sta=553.2,594.6
XS Rating Curve= 0 ,0
Exp/Cntr=0.3,0.1

Type RM Length L Ch R = 1 ,5324    ,410.3,416.9,417.6
XS GIS Cut Line= 2
2468809.03848393584328.6231831732469747.17373478584674.763844004
#Sta/Elev= 30
       0 1785.28    40.2 1762.55    65.8 1749.52    78.6 1745.42   138.3 1732.87
     190 1717.32   202.2 1709.25   224.2 1688.92   230.4 1684.74   244.8 1682.45
   264.7 1683.47   313.1 1683.33   342.9 1687.72   368.5 1682.84   419.7 1682.95
   436.7 1685.46   509.2 1685.39   556.1 1682.65   590.2 1686.02   675.5 1685.97
   722.4 1688.42   730.9 1690.64   742.3 1695.58   760.7 1707.51   777.8 1708.75
   781.7 1710.11   794.8 1718.82   884.4 1757.15   935.5 1772.76    1000 1784.02
#Mann= 8 ,-1 , 0
       0      .1       0  123.35      .1       0   230.4    .045       0
   264.7      .1       0  579.62     .05       0  693.69      .1       0
  701.02     .06       0  901.69      .1       0
Bank Sta=230.4,264.7
XS Rating Curve= 0 ,0
Exp/Cntr=0.3,0.1

Type RM Length L Ch R = 1 ,4907    ,258.2,253.3,247.6
XS GIS Cut Line= 2
2468628.63412151584635.4675320112469472.79720852585115.126376015
#Sta/Elev= 30
       0 1802.63    33.4 1797.48      53  1792.6    68.6 1786.88   118.5 1764.13
   140.4 1752.85   209.3 1709.08   250.9 1688.99   265.2 1679.61   269.3 1677.96
   283.1 1678.89   301.5 1677.06     318 1678.76   324.5 1680.66   370.5 1678.67
     403 1679.25   470.5 1677.47   513.1 1679.41   617.2 1675.81   719.9  1680.5
   733.9 1686.53   752.1  1700.2   756.9 1702.62   779.9 1704.85   798.3 1717.03
   830.5 1725.63   863.6 1739.94   904.7 1746.24   946.2 1748.14   970.9  1752.4
#Mann= 8 ,-1 , 0
       0     .05       0  174.48      .1       0   283.1    .045       0
     318      .1       0  429.41     .05       0  732.48    .055       0
  811.81     .06       0  889.38      .1       0
Bank Sta=283.1,318
XS Rating Curve= 0 ,0
Exp/Cntr=0.3,0.1

Type RM Length L Ch R = 1 ,4654    ,353.3,356.3,358.3
XS GIS Cut Line= 2
2468524.96595976584905.1016937562469506.78657304 585234.39203449
#Sta/Elev= 30
       0  1791.6    69.4 1777.96    94.7 1769.24   115.8 1759.04     145  1742.8
   211.3 1701.79   233.9 1691.52     265  1686.3   305.6 1676.95   326.7 1675.22
   352.1 1675.15   360.5 1677.67   373.1 1675.16     390 1676.98   415.3 1675.69
   558.9 1674.06   584.3    1675     601  1683.8     660 1704.68   672.6 1705.05
   682.1 1708.89     698 1708.82   710.5 1715.39   723.3 1717.74   803.5 1728.03
   816.1 1732.09   879.4  1747.2   938.5 1757.76   963.3 1763.52  1035.6 1785.27
#Mann= 8 ,-1 , 0
       0      .1       0   93.57      .1       0   326.7    .045       0
   352.1      .1       0  542.47     .05       0  654.69    .055       0
   657.6     .06       0  766.91      .1       0
Bank Sta=326.7,352.1
XS Rating Curve= 0 ,0
Exp/Cntr=0.3,0.1

Type RM Length L Ch R = 1 ,4298    ,267.8,269.7,412.3
XS GIS Cut Line= 2
2468450.92892527585201.1717742332469315.90534727585475.476254509
#Sta/Elev= 30
       0 1776.66     8.2 1770.79    20.8 1767.24    45.8 1749.78    90.4 1720.81
   131.8 1696.24   146.7 1691.45   180.2  1674.4   188.6 1670.46   214.7 1671.26
   243.2 1672.26   285.2  1670.5   306.1 1671.38   314.5  1670.2   336.5 1672.72
   360.7 1673.58   532.7 1671.04   587.3 1671.44   595.7 1672.42   600.2 1674.43
   612.5 1692.84   637.6 1706.53   657.5 1707.88   676.6 1712.31   702.1 1716.25
   746.7 1726.53   756.3 1727.64   772.2 1734.38   848.7 1762.19   907.4 1782.13
#Mann= 10 ,-1 , 0
       0      .1       0   47.42      .1       0  116.48      .1       0
   180.2    .045       0   214.7      .1       0   266.6      .1       0
  485.77    .025       0  561.57     .06       0  672.84    .055       0
  704.95      .1       0
Bank Sta=180.2,214.7
XS Rating Curve= 0 ,0
Exp/Cntr=0.3,0.1

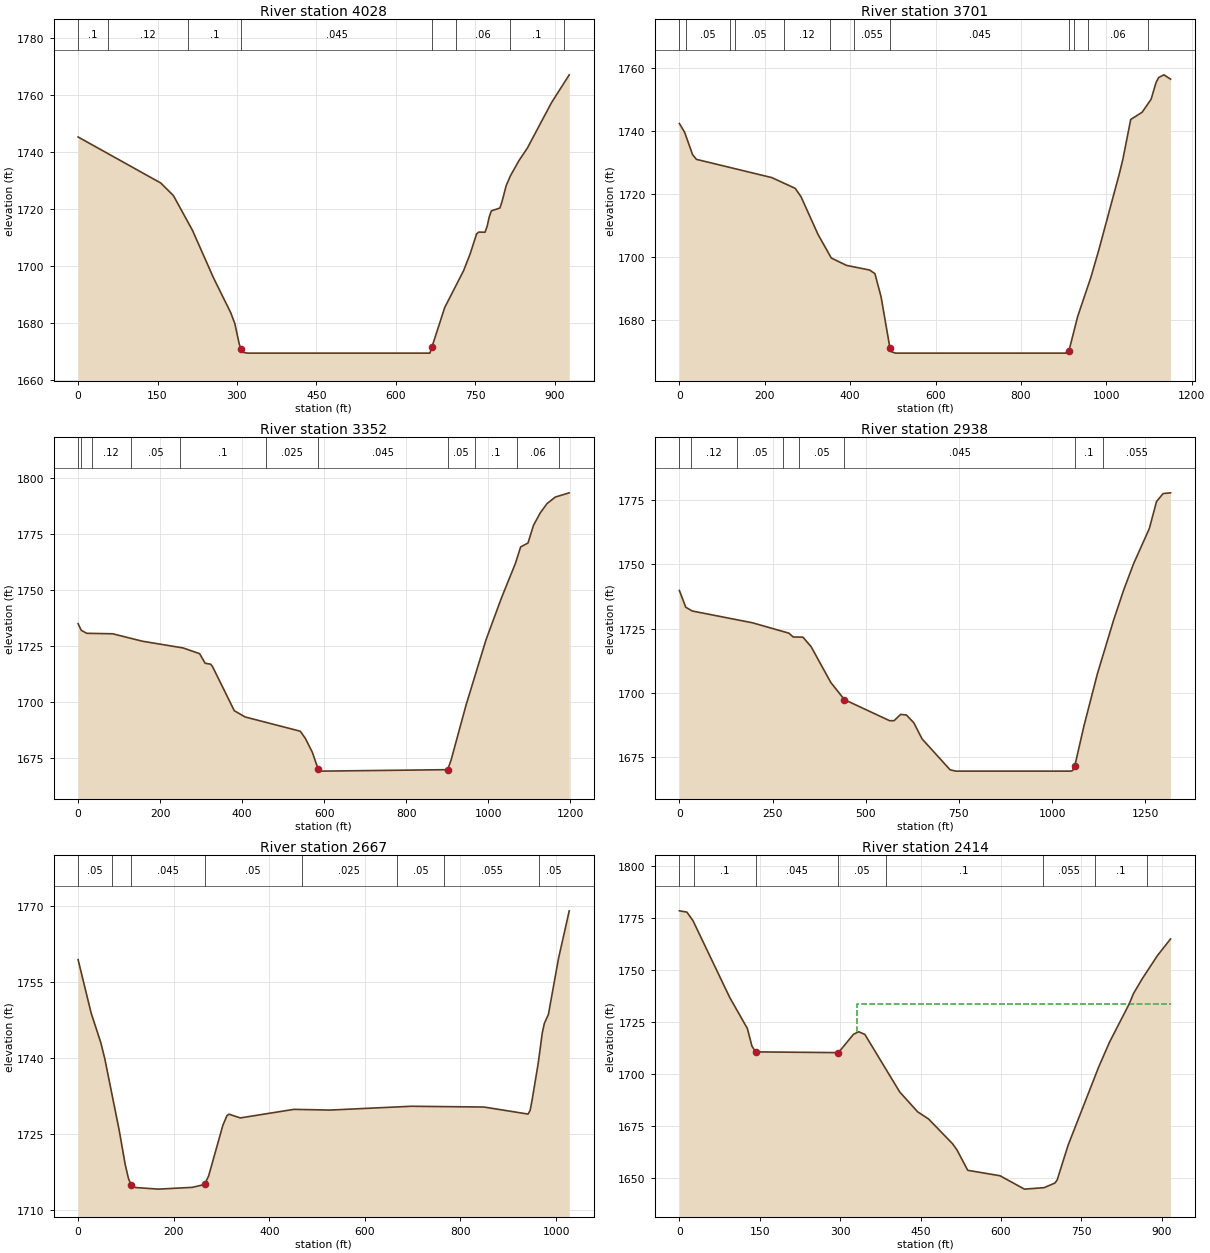
Type RM Length L Ch R = 1 ,4028    ,283.3,326.6,434.1
XS GIS Cut Line= 3
2468360.80182676585384.5251230712468465.49770437585514.281499086
2469225.60074785585542.907928928
#Sta/Elev= 30
       0 1745.33     156 1729.16     180 1724.72     216  1712.5     256 1695.68
   288.1  1683.6   296.1 1679.65   304.1 1672.68   307.4 1670.75   312.1 1669.59
   320.1 1669.34   664.3 1669.34   668.3 1671.59   692.3 1685.39   727.9 1698.32
   740.4  1704.3   752.4 1711.23   756.4 1711.89   768.4 1711.85   772.4 1713.94
   776.4 1717.27   780.4 1719.37   796.4 1720.34   800.4 1722.55   808.4 1728.27
   816.4  1731.7   832.4    1737   848.5 1741.48   893.7 1757.33   927.4 1767.18
#Mann= 8 ,-1 , 0
       0      .1       0    56.4     .12       0  207.91      .1       0
   307.4    .045       0   668.3    .025       0  714.43     .06       0
  815.73      .1       0  917.04      .1       0
Bank Sta=307.4,668.3
XS Rating Curve= 0 ,0
Exp/Cntr=0.3,0.1

Type RM Length L Ch R = 1 ,3701    ,239.5,348.9,493.2
XS GIS Cut Line= 3
2468354.37238751585422.4629783082468252.56933256585661.917440622
2469054.79983251586047.712493337
#Sta/Elev= 30
       0  1742.3    12.2 1739.52    30.9  1732.4    39.9 1730.91   216.6 1725.11
   271.3 1721.69   284.8 1719.06   324.7 1707.04   355.8 1699.56   391.4 1697.22
   445.4 1695.75   457.9 1694.61   472.4 1687.23   493.3 1670.83   497.9  1669.7
   506.7 1669.34     904 1669.34   912.6 1670.17   932.8 1680.96   963.9 1693.47
   981.9 1701.88  1030.5 1726.36  1038.8 1730.99  1057.1 1743.58  1083.8 1745.88
  1104.8 1749.99  1116.7 1755.43  1122.7 1756.92  1134.9 1757.77  1150.4  1756.4
#Mann= 12 ,-1 , 0
       0      .1       0   14.49     .05       0  118.57     .12       0
  129.32     .05       0  244.15     .12       0  352.31      .1       0
  408.28    .055       0   493.3    .045       0   912.6      .1       0
  924.72    .055       0  957.73     .06       0 1096.87      .1       0
Bank Sta=493.3,912.6
XS Rating Curve= 0 ,0
Exp/Cntr=0.3,0.1

Type RM Length L Ch R = 1 ,3352    ,245.9,414.6,266.1
XS GIS Cut Line= 3
2468313.00770002585436.0834329072468185.29400477585679.611952422
 2468588.6003511586509.402384524
#Sta/Elev= 30
       0 1735.12     7.7  1732.2    21.2 1730.85    84.5 1730.63   156.7 1727.32
   256.1 1724.31   296.4 1721.75   309.8 1717.47   323.1 1717.08   327.6 1716.06
   380.9  1696.3   407.2 1693.52   541.9 1687.14   554.4 1683.86   571.1 1677.78
   585.5 1670.17   594.4 1669.34   901.3 1669.99   909.7 1674.39   945.7 1698.64
   994.7 1727.97  1032.7  1746.8  1066.4 1762.07  1079.2 1769.42    1097 1771.13
  1110.5 1779.06  1126.9 1784.58  1143.4 1788.72  1163.7 1791.66  1197.6 1793.54
#Mann= 11 ,-1 , 0
       0      .1       0    6.46     .05       0   33.74     .12       0
  127.79     .05       0  249.12      .1       0  457.31    .025       0
   585.5    .045       0   901.3     .05       0   967.5      .1       0
 1069.53     .06       0 1171.57     .05       0
Bank Sta=585.5,901.3
XS Rating Curve= 0 ,0
Exp/Cntr=0.3,0.1

Type RM Length L Ch R = 1 ,2938    ,336.9,270.6,711.6
XS GIS Cut Line= 3
2468286.30617365  585419.32130042468041.46904762585977.051520841
2468347.35190425586616.415303846
#Sta/Elev= 30
       0 1739.85      17 1733.32    34.5 1731.84   196.1 1727.24   293.8 1723.19
   305.3  1721.7   331.5 1721.63   353.4 1717.92   406.1 1703.98   442.81697.247
     564 1689.03   576.1 1689.03   593.6 1691.48   609.1 1691.25   628.9 1688.23
   651.1 1681.93   726.4 1669.86   741.8 1669.34  1050.1 1669.34  1055.3 1669.57
  1060.9 1671.33  1085.6 1687.02  1121.8 1707.44  1165.4 1728.41    1192 1739.99
  1218.6 1750.26  1260.9 1764.01  1280.3 1774.57  1297.9 1777.68  1317.9 1777.97
#Mann= 8 ,-1 , 0
       0      .1       0   32.41     .12       0  154.65     .05       0
   276.9      .1       0  320.95     .05       0   442.8    .045       0
  1060.9      .1       0 1137.37    .055       0
Bank Sta=442.8,1060.9
XS Rating Curve= 0 ,0
Exp/Cntr=0.3,0.1

Type RM Length L Ch R = 1 ,2667    ,116.3,102,94.9
XS GIS Cut Line= 2
2467764.28296039585654.3008738052468115.85258465586619.880723102
#Sta/Elev= 30
       0 1759.48    27.3 1748.93    47.5  1743.1      56 1739.86    85.8 1725.89
    98.5 1719.07   105.4 1716.26   111.3 1714.93   119.8 1714.49   167.8 1714.17
     239 1714.52   264.5 1715.09   273.1 1716.77   302.9 1726.77   311.3 1728.65
   315.6 1728.97   339.4 1728.23   451.5 1729.92   526.7 1729.78     697 1730.53
     849 1730.38   941.4 1728.99   945.7 1729.69   949.9 1731.74   962.7 1739.03
   971.2 1745.02   975.5 1746.89     984 1748.65  1005.3 1759.78  1027.6 1769.12
#Mann= 8 ,-1 , 0
       0     .05       0   70.16      .1       0   111.3    .045       0
   264.5     .05       0  467.81    .025       0  666.66     .05       0
  766.07    .055       0   964.9     .05       0
Bank Sta=111.3,264.5
XS Rating Curve= 0 ,0
Exp/Cntr=0.3,0.1

Type RM Length L Ch R = 1 ,2414    ,100.4,66.7,48.2
XS GIS Cut Line= 3
2467473.05040176585845.2127732232467722.72630587586089.076326897
2467825.11982214586646.899482304
#Sta/Elev= 30
       0 1778.43    13.9 1777.82    25.3 1773.71      94 1736.75   126.8 1721.91
   135.3 1713.45   142.2 1710.68   296.6 1710.32   324.8 1719.15   334.4 1720.35
   345.9 1719.08     411 1691.43   444.4  1681.9   464.7 1678.47   509.5 1666.57
   517.6 1663.67   537.9  1653.8     598 1651.19   643.7 1644.76   680.3 1645.46
   700.6  1647.7   704.7 1649.17     725 1665.79   781.9 1703.27   802.3 1715.32
   838.9 1733.64     847 1738.67   863.3 1745.78   891.7 1756.92   916.2 1764.93
#Mann= 8 ,-1 , 0
       0      .1       0   27.99      .1       0   142.2    .045       0
   296.6     .05       0  384.72      .1       0  677.42    .055       0
  774.99      .1       0  872.55    .055       0
#XS Ineff= 2 , 0
                          331.58         1733.52
Permanent Ineff=
       F       F
Bank Sta=142.2,296.6
XS Rating Curve= 0 ,0
Exp/Cntr=0.3,0.1