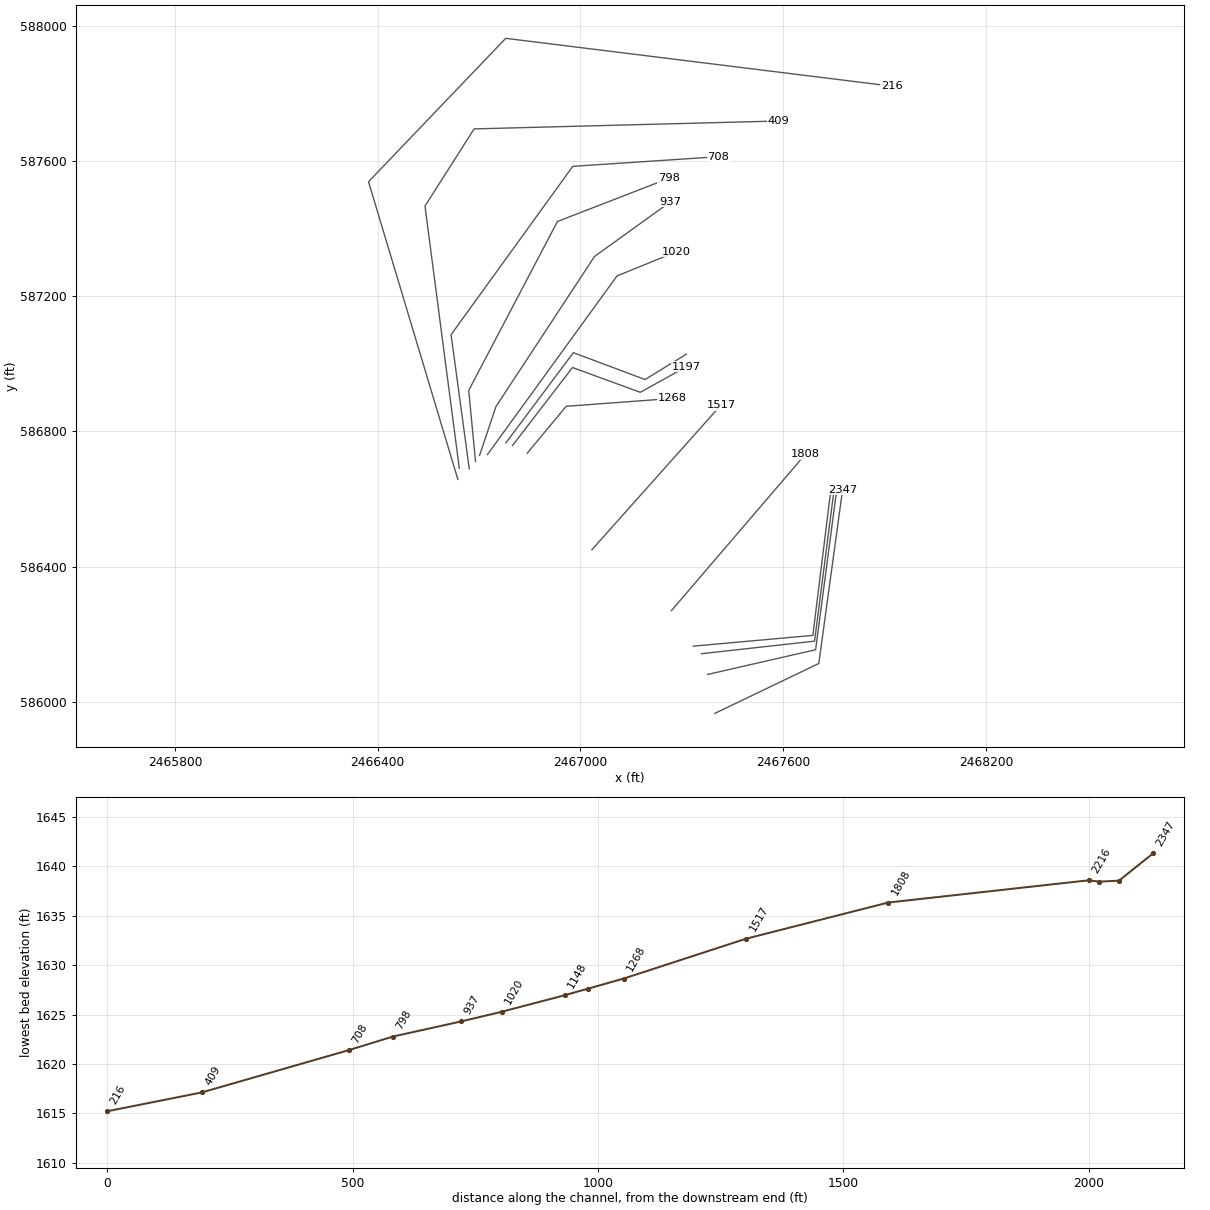
HEC-RAS study MILLERRN.prj: MILLERRN

--- MILLERRN.g01 (geometry) --- (continued)

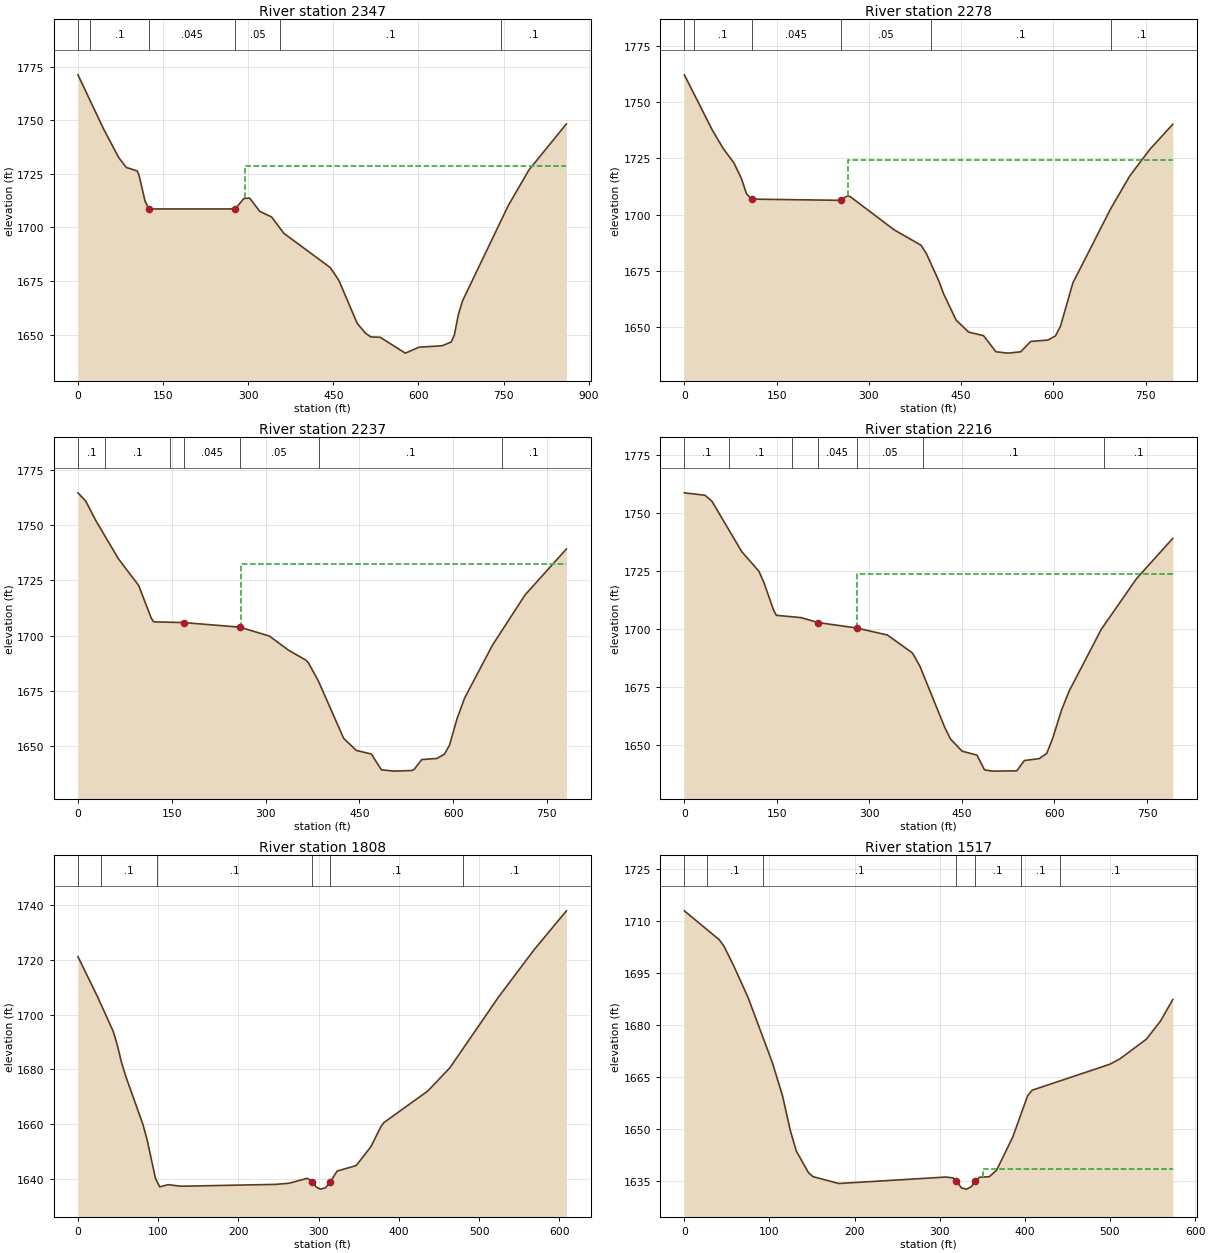
Type RM Length L Ch R = 1 ,2347    ,91,69.5,56
XS GIS Cut Line= 3
2467397.95886775 585965.641258352467705.50452938586113.317369002
2467775.95551795586628.151516232
#Sta/Elev= 30
       0  1771.2    45.2 1745.91    71.9 1732.55    85.2 1727.96   104.5 1726.34
   107.4 1724.54   118.4 1712.09   125.1 1708.61   277.3 1708.61   292.3  1713.5
   302.6 1713.68   320.4 1707.48   341.2 1704.88   362.9 1697.22   444.5 1681.27
   459.8  1675.3   492.1 1655.21     507 1650.54   516.4 1648.86   532.5 1648.72
   576.9 1641.31   601.1 1644.08   641.5 1644.74   657.7 1646.48   663.3 1649.72
   670.4 1659.29   677.8 1665.74   758.6  1710.3   794.9 1726.85   860.8  1748.3
#Mann= 6 ,-1 , 0
       0      .1       0   21.99      .1       0   125.1    .045       0
   277.3     .05       0  355.55      .1       0  745.74      .1       0
#XS Ineff= 2 , 0
                          294.74         1728.68
Permanent Ineff=
       F       F
Bank Sta=125.1,277.3
XS Rating Curve= 0 ,0
Exp/Cntr(USF)=0,0
Exp/Cntr=0.3,0.1

Type RM Length L Ch R = 1 ,2278    ,70.3,40.8,33.8
XS GIS Cut Line= 3
 2467376.2816405586080.8015281252467696.02074246586153.962170099
2467756.98794411586615.958075903
#Sta/Elev= 30
       0 1762.11    45.2 1737.69    63.2 1729.39    80.6 1722.98    92.8 1716.04
     101  1709.3   109.2 1706.92   254.2 1706.39   265.1 1708.39   269.2 1708.11
     341  1693.3   384.7 1686.46   393.5  1682.7   413.7 1670.57   421.7 1664.71
   441.9 1653.16   462.1  1647.9   486.3 1646.31   506.5 1639.15   525.8 1638.55
   546.8 1639.14   562.9 1643.72   591.2 1644.37   603.3 1646.22   611.4 1650.49
   631.5 1669.68   693.1 1702.71   724.3 1717.31   756.6    1729     794 1740.16
#Mann= 6 ,-1 , 0
       0      .1       0   15.57      .1       0   109.2    .045       0
   254.2     .05       0  401.23      .1       0   693.9      .1       0
#XS Ineff= 2 , 0
                          266.67         1724.28
Permanent Ineff=
       F       F
Bank Sta=109.2,254.2
XS Rating Curve= 0 ,0
Exp/Cntr(USF)=0,0
Exp/Cntr=0.3,0.1

Type RM Length L Ch R = 1 ,2237    ,31.9,20.3,19
XS GIS Cut Line= 3
2467358.38431405586142.2070111342467692.90942596586179.376468013
2467749.69609619586620.247525993
#Sta/Elev= 30
       0 1764.76    12.4 1761.04    28.5  1752.2    64.8 1734.79      97 1722.75
   117.1 1707.96   121.1  1706.2   169.4 1705.87   258.81703.793   306.2 1699.75
   336.6 1693.36   364.3 1688.87   368.4 1687.68   384.5 1679.36   424.8 1653.38
     445 1647.87   469.2 1646.21   485.3 1639.04   505.5 1638.45   533.7 1638.73
   537.7 1639.24   549.8  1643.7     574  1644.2   586.1 1646.16   594.2 1650.27
   606.3 1662.31   618.4 1671.66   662.9 1695.64   715.2 1718.49   781.1 1739.27
#Mann= 7 ,-1 , 0
       0      .1       0   43.51      .1       0   146.6      .1       0
   169.4    .045       0   258.8     .05       0  385.17      .1       0
  677.86      .1       0
#XS Ineff= 2 , 0
                          260.91         1732.61
Permanent Ineff=
       F       F
Bank Sta=169.4,258.8
XS Rating Curve= 0 ,0
Exp/Cntr(USF)=0,0
Exp/Cntr=0.3,0.1

Type RM Length L Ch R = 1 ,2216    ,399.9,408.6,425.2
XS GIS Cut Line= 3
2467334.18343614586164.570405239 2467687.9051194586196.437223551
2467741.44137416586629.825952591
#Sta/Elev= 30
       0 1758.83    33.4 1757.78    44.7  1755.2    92.9 1733.47     121 1724.89
   129.1 1719.96   145.1 1707.82   149.2  1705.9   189.3 1704.91   216.3  1702.8
   279.71700.415   329.1  1697.4   369.7 1689.66   381.8 1683.96   422.1 1657.48
   431.6 1652.39   450.3 1647.21   474.3 1645.52   486.6 1639.12   499.8 1638.59
     539 1638.71   551.1 1643.17   575.3    1644   587.4 1646.23   596.7 1652.46
   611.5    1665   623.6  1673.1     676 1699.93     733 1721.76   791.8 1739.17
#Mann= 7 ,-1 , 0
       0      .1       0   71.62      .1       0  174.14      .1       0
   216.3    .045       0   279.7     .05       0  387.65      .1       0
  680.38      .1       0
#XS Ineff= 2 , 0
                          280.15         1723.73
Permanent Ineff=
       F       F
Bank Sta=216.3,279.7
XS Rating Curve= 0 ,0
Exp/Cntr(USF)=0,0
Exp/Cntr=0.3,0.1

Type RM Length L Ch R = 1 ,1808    ,290.6,290.4,289.9
XS GIS Cut Line= 2
2467269.14916198 586269.470984122467665.19904356586731.838399274
#Sta/Elev= 30
       0  1721.2    24.8  1706.3      44 1693.89    49.3 1688.59    54.5 1682.34
    59.8 1677.35    80.9 1660.02    86.1  1654.5    96.7 1640.17   101.9 1637.18
   112.5 1637.97   128.3  1637.4   246.1 1638.07   263.1 1638.49   285.8 1640.28
   292.1 1639.08   297.2 1637.04   302.1 1636.34   308.5 1636.83   314.2 1638.84
   323.1 1642.95   346.8 1644.93   365.3 1651.91   377.5 1659.09   381.1 1660.58
   436.2 1672.18   463.6 1680.65   524.1  1706.4   568.1 1723.54   608.8 1737.91
#Mann= 6 ,-1 , 0
       0      .1       0    28.9      .1       0   98.07      .1       0
   292.1    .045       0   314.2      .1       0  479.62      .1       0
Bank Sta=292.1,314.2
XS Rating Curve= 0 ,0
Exp/Cntr=0.3,0.1

Type RM Length L Ch R = 1 ,1517    ,266.6,249,233.6
XS GIS Cut Line= 2
2467034.01530426586449.9240159062467415.97929868586878.115280388
#Sta/Elev= 30
       0 1712.85    40.9 1704.54    46.5 1702.69    57.9 1697.04    74.9 1687.84
   103.2 1669.25   115.3 1659.58   124.6 1649.42   131.5 1643.66     146 1637.33
   151.3 1636.25   181.4 1634.29   307.2 1636.15   315.7  1635.9   319.6 1635.02
   325.6    1633   331.6 1632.67   337.6 1633.48   341.2  1634.9   346.8  1636.1
   358.2 1636.25   366.7 1638.09   385.7 1647.63   403.3  1659.6   408.7 1661.18
   499.8 1668.65   511.9 1670.23   542.7 1675.86   559.3 1681.07   573.8  1687.3
#Mann= 7 ,-1 , 0
       0      .1       0   26.21      .1       0   92.19      .1       0
   319.6    .045       0   341.2      .1       0  395.65      .1       0
   440.7      .1       0
#XS Ineff= 2 , 0
                          350.58          1638.6
Permanent Ineff=
       F       F
Bank Sta=319.6,341.2
XS Rating Curve= 0 ,0
Exp/Cntr=0.3,0.1

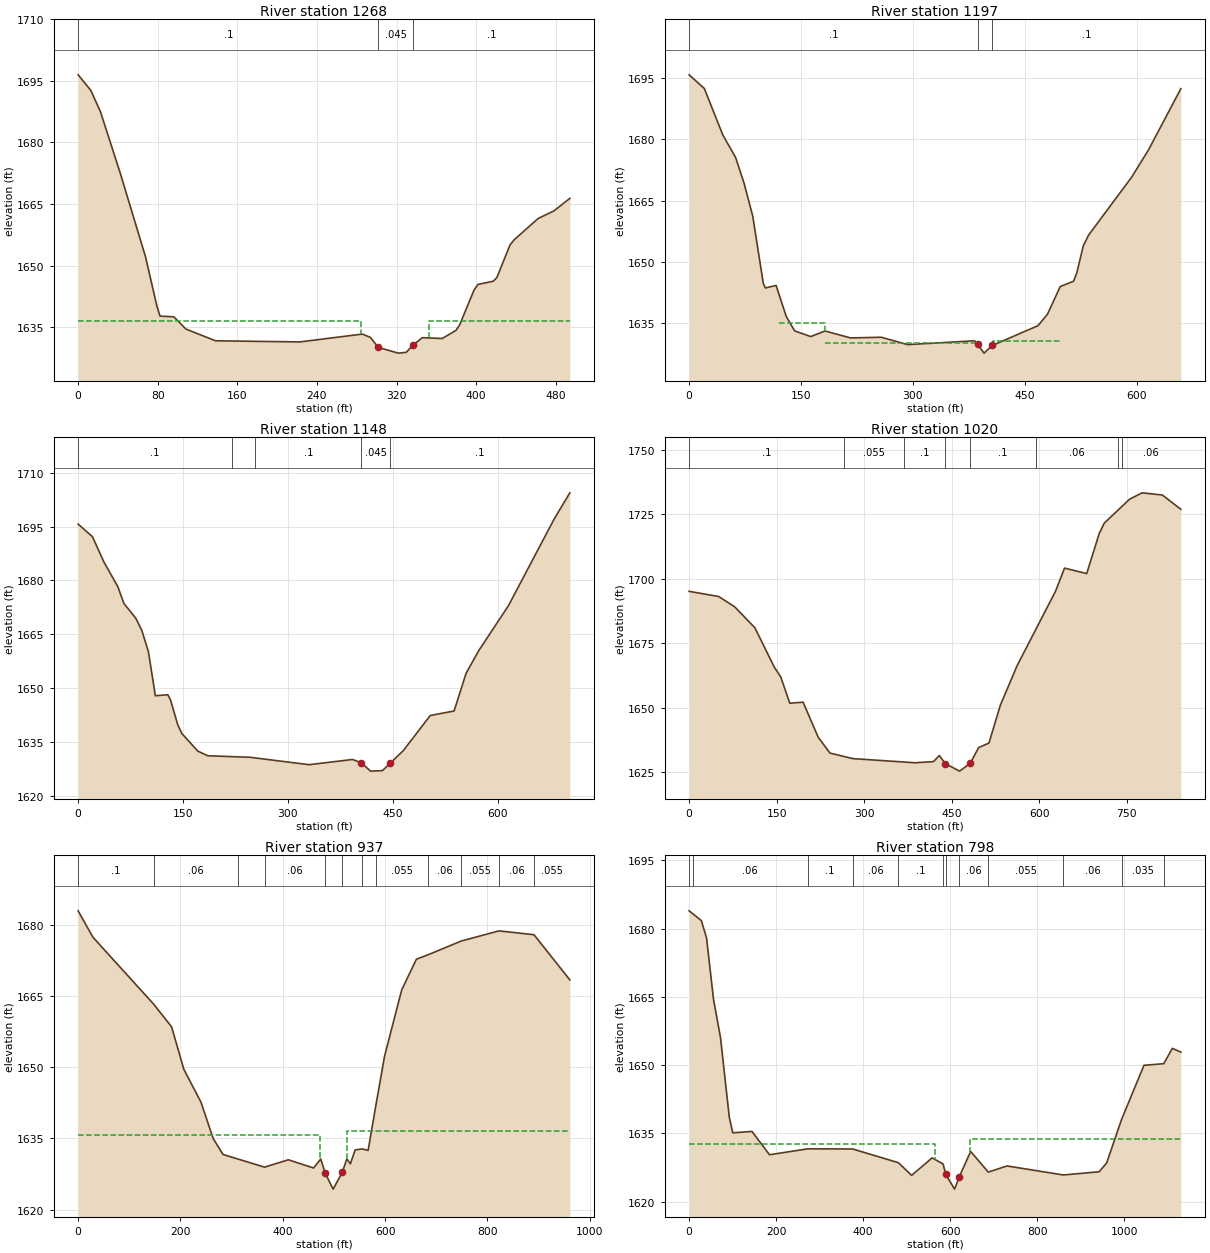
Type RM Length L Ch R = 1 ,1268    ,76.9,71.9,67.8
XS GIS Cut Line= 3
2466842.55255353586735.5616882822466957.94370325586874.411478322
2467270.64103862586897.489708264
#Sta/Elev= 30
       0 1696.48    12.8 1692.67    22.4 1687.51    42.3 1672.54    67.8 1652.05
    79.2 1640.06    82.3 1637.67    96.2 1637.49   108.3 1634.51     138 1631.65
   222.8 1631.37   285.6 1633.28   293.6 1632.49   301.7 1630.03   321.7 1628.64
   329.7 1628.84   336.8 1630.64   345.8 1632.41   365.8  1632.2   379.7 1634.19
   383.4 1635.53   397.9 1644.06   401.9  1645.4   417.1 1646.16   420.8 1647.08
     434 1655.02     438 1656.23   462.1 1661.44   478.1 1663.31   494.1 1666.37
#Mann= 3 ,-1 , 0
       0      .1       0   301.7    .045       0   336.8      .1       0
#XS Ineff= 2 ,-1
       0  284.35 1636.43     353494.0869 1636.43
Permanent Ineff=
       F       F
Bank Sta=301.7,336.8
XS Rating Curve= 0 ,0
Exp/Cntr(USF)=0,0
Exp/Cntr=0.5,0.3

Type RM Length L Ch R = 1 ,1197    ,57.1,48.5,44.3
XS GIS Cut Line= 4
2466799.40257681586758.6782806622466976.49970785586989.147149829
2467177.25022284 586915.761009912467312.49905922586990.966640901
#Sta/Elev= 30
       0  1695.8    20.4 1692.46    45.3 1681.02    62.4 1675.54    73.8 1669.17
    85.3  1661.2    99.5 1644.66   102.4 1643.59   116.6 1644.22   130.2 1636.62
   141.5 1633.07     163 1631.69   182.2 1633.05   216.5 1631.35   257.5 1631.52
     293 1629.71   382.5 1630.66   386.7 1629.79   395.3 1627.63   406.4  1629.5
   467.7 1634.36   480.4 1637.17   497.5 1643.95   515.3 1645.24   519.6 1647.25
   528.4 1653.93   535.5 1656.54   593.1 1670.71     616 1677.48   659.1  1692.4
#Mann= 3 ,-1 , 0
       0      .1       0   386.7    .045       0   406.4      .1       0
#XS Ineff= 3 ,-1
     120     182    1635     182     386    1630     407     500  1630.5
Permanent Ineff=
       F       F       F
Bank Sta=386.7,406.4
XS Rating Curve= 0 ,0
Exp/Cntr(USF)=0,0
Exp/Cntr=0.5,0.3

Type RM Length L Ch R = 1 ,1148    ,93.6,128.2,157.5
XS GIS Cut Line= 4
2466779.68059293586766.4543558182466979.12003579587033.038684448
2467191.39399423586953.5875742872467313.52478924587028.679415336
#Sta/Elev= 30
       0 1695.69    20.5 1692.17    36.8 1685.16    56.8 1678.26    65.5 1673.58
    82.5 1669.49    91.1 1666.07   100.5 1660.19   110.4 1647.92   128.2  1648.2
     132 1646.82   142.5 1639.83   148.2 1637.43   171.1 1632.52   185.4 1631.22
   245.5 1630.81   330.2 1628.74   392.3 1630.19   405.1 1629.24     418 1626.95
     435 1627.08   446.2 1629.16   464.9 1632.65   503.4 1642.42   537.5 1643.68
   554.6 1654.14   572.9 1660.52   615.2 1672.98   680.9 1697.21     703 1704.38
#Mann= 5 ,-1 , 0
       0      .1       0   219.4    .055       0  252.99      .1       0
   405.1    .045       0   446.2      .1       0
Bank Sta=405.1,446.2
XS Rating Curve= 0 ,0
Exp/Cntr=0.5,0.3

Type RM Length L Ch R = 1 ,1020    ,81.1,82.6,82.5
XS GIS Cut Line= 3
2466724.98475003586731.6945356582467108.28999863587260.106415765
2467284.09720236587331.789083324
#Sta/Elev= 30
       0 1695.14    50.7 1693.13    78.1 1689.12   112.7 1680.98   146.1 1665.66
   157.1 1661.89   172.5 1651.68   195.4 1652.06   221.2 1638.47   241.4 1632.29
   280.7 1630.14   387.3 1628.53   418.8 1628.98   428.9 1631.34   438.9 1628.22
   463.5 1625.28   481.8  1628.3   496.2 1634.43   513.9 1636.19   533.4 1650.89
   562.3 1666.34   627.9 1695.14   643.4 1704.16   681.4 1702.03   702.8 1717.56
   711.6 1721.65   754.8 1730.92   776.4 1733.41     811 1732.56   842.7 1727.02
#Mann= 8 ,-1 , 0
       0      .1       0  265.75    .055       0  367.96      .1       0
   438.9    .045       0   481.8      .1       0  594.51     .06       0
  735.32    .055       0  741.42     .06       0
Bank Sta=438.9,481.8
XS Rating Curve= 0 ,0
Exp/Cntr=0.5,0.3

Type RM Length L Ch R = 1 ,937     ,138.3,139.1,140.8
XS GIS Cut Line= 4
2466701.57056694586729.0966199442466750.15145613586873.735176393
2467041.63679126587317.5878457992467266.87545932587479.892180134
#Sta/Elev= 30
       0 1683.01    28.8 1677.46   147.6 1663.33   182.7 1658.54   206.6 1649.59
   240.1 1642.65     264 1634.98   283.2 1631.61   312.7 1630.64   364.5 1628.94
   410.9 1630.49   460.2 1628.76   474.3 1630.65   483.1 1627.63   498.5  1624.3
   516.2 1627.81   525.3 1630.69   532.2 1629.64   541.6 1632.58   555.3 1632.78
   566.9 1632.47   581.3 1641.53     599 1652.36   632.5 1666.32   661.2  1672.8
   683.6 1673.72     749 1676.64   822.7 1678.78   891.1 1677.97   961.2 1668.44
#Mann= 12 ,-1 , 0
       0      .1       0   147.6     .06       0   312.7    .055       0
   364.5     .06       0   483.1    .045       0   516.2     .01       0
   555.3      .1       0   581.3    .055       0   683.6     .06       0
     749    .055       0   822.7     .06       0   891.1    .055       0
#XS Ineff= 2 , 0
          473.39  1635.8  525.42          1636.5
Permanent Ineff=
       F       F
Bank Sta=483.1,516.2
XS Rating Curve= 0 ,0
Exp/Cntr(USF)=0,0
Exp/Cntr=0.5,0.3

Type RM Length L Ch R = 1 ,798     ,93.5,90.2,84.9
XS GIS Cut Line= 4
2466689.59081827586711.0169981222466669.47350195 586921.41498191
2466931.91973304587421.1753455762467261.75631148587549.071161705
#Sta/Elev= 30
       0 1683.91     7.9 1683.33    28.2 1681.75    40.1 1677.96    56.1 1664.47
    72.2 1656.03    92.3 1638.58   100.3 1635.14   144.5 1635.44   184.7 1630.32
   272.6 1631.62   375.7 1631.59   480.8 1628.58   511.2 1625.79   558.2 1629.63
   583.5  1628.3   589.6    1626   609.8 1622.77     621 1625.54   646.8 1631.05
   687.3 1626.51   730.3 1627.86   859.7 1625.88   941.9 1626.58   959.1  1628.5
   993.4 1638.06  1044.9 1649.97  1090.4 1650.33  1110.1  1653.7  1129.6 1652.87
#Mann= 12 ,-1 , 0
       0      .1       0     7.9     .06       0   272.6      .1       0
   375.7     .06       0   480.8      .1       0   583.5     .06       0
   589.6    .045       0     621     .06       0   687.3    .055       0
   859.7     .06       0   993.4    .035       0  1090.4    .055       0
#XS Ineff= 2 , 0
          565.98 1632.77  645.21         1633.84
Permanent Ineff=
       F       F
Bank Sta=589.6,621
XS Rating Curve= 0 ,0
Exp/Cntr(USF)=0,0
Exp/Cntr=0.5,0.3

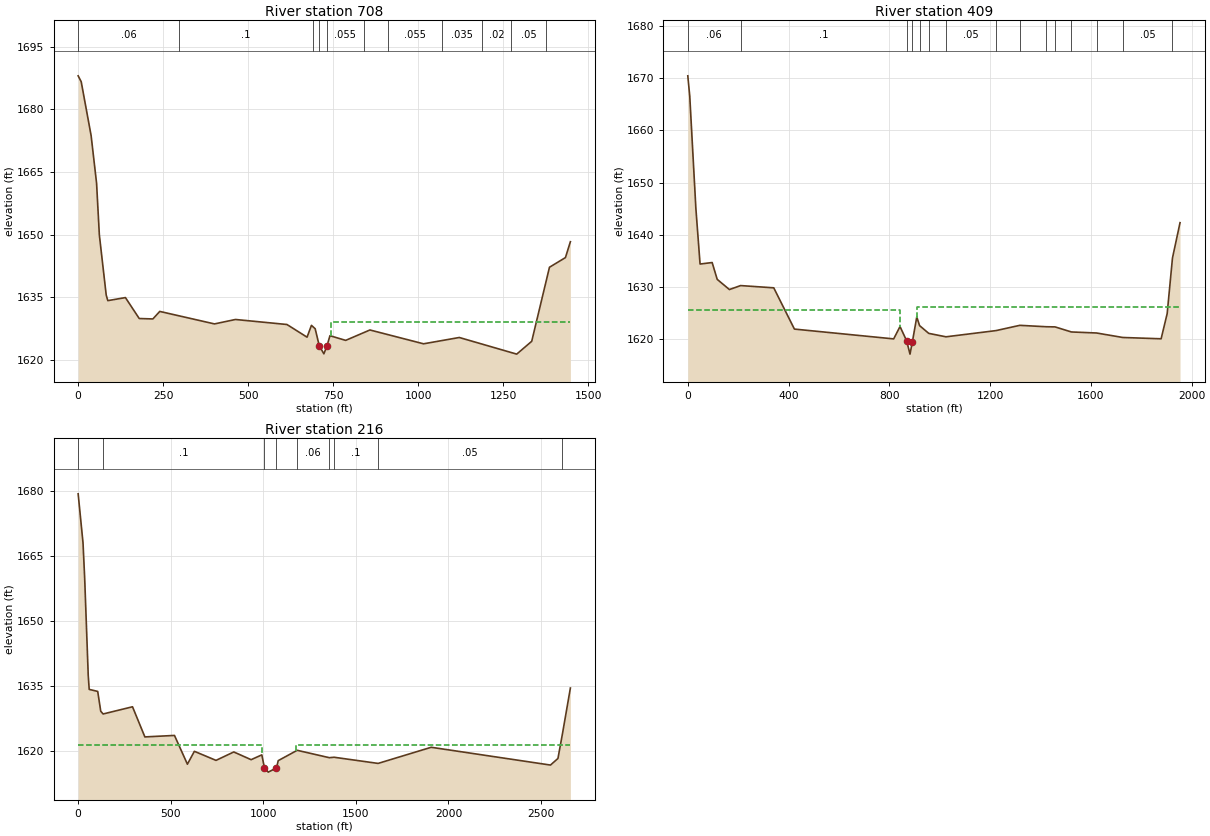
Type RM Length L Ch R = 1 ,708     ,298.2,299.5,299.6
XS GIS Cut Line= 4
2466671.07958173586689.1400822052466617.22871178 587086.29024808
2466977.35640456 587584.410795112467408.16336416 587613.01906977
#Sta/Elev= 30
       0 1687.99       9 1686.58    38.1  1673.7    54.2 1662.28    62.3 1649.93
    82.5 1635.53    87.2 1634.19     139 1634.92   179.6 1629.91   219.7 1629.81
   239.9 1631.61   400.8 1628.62   462.5 1629.68   613.8 1628.48     673 1625.45
   685.9 1628.28   696.9 1627.46   708.8 1623.41   722.4 1621.46   731.7 1623.39
   740.3  1625.8   786.5 1624.68   857.8 1627.17  1015.5 1623.86  1120.6 1625.37
  1289.4 1621.39  1333.5 1624.46  1385.7 1642.18  1432.6 1644.49  1447.2 1648.29
#Mann= 11 ,-1 , 0
       0     .06       0  295.12      .1       0  690.75     .06       0
   708.8    .045       0   731.7    .055       0  838.98     .05       0
  912.12    .055       0 1069.81    .035       0 1188.72     .02       0
 1273.67     .05       0  1375.6     .06       0
#XS Ineff= 2 , 0
                          742.28         1628.96
Permanent Ineff=
       F       F
Bank Sta=708.8,731.7
XS Rating Curve= 0 ,0
Exp/Cntr(USF)=0,0
Exp/Cntr=0.3,0.1

Type RM Length L Ch R = 1 ,409     ,193.9,192.3,163.2
XS GIS Cut Line= 4
2466641.57102246 586691.111474652466540.00045157587466.741288732
2466685.43104171587695.2750732382467585.81395315587718.627322023
#Sta/Elev= 30
       0 1670.46     7.8 1666.55    32.1 1645.01    48.7 1634.38    96.6 1634.67
   116.8 1631.44   165.2 1629.49   209.6 1630.25   341.2 1629.82   423.2 1621.91
   817.2 1620.03   842.3  1622.4   868.4  1619.7     882 1617.11   891.3 1619.44
   908.9 1624.24   919.9 1622.58   956.3 1621.09  1024.8 1620.43  1223.3 1621.62
  1317.8 1622.63  1422.6 1622.36  1457.5 1622.33  1522.6 1621.36  1622.6 1621.16
  1726.7  1620.3  1878.7 1620.05  1902.7 1624.87  1923.8 1635.54  1953.8 1642.31
#Mann= 15 ,-1 , 0
       0     .06       0   209.6      .1       0   868.4    .045       0
   891.3      .1       0   919.9     .06       0   956.3    .055       0
  1024.8     .05       0  1223.3    .055       0  1317.8    .035       0
  1422.6     .02       0  1457.5    .035       0  1522.6     .02       0
  1622.6    .055       0  1726.7     .05       0  1923.8     .06       0
#XS Ineff= 2 , 0
          841.16 1625.62   910.2         1626.11
Permanent Ineff=
       F       F
Bank Sta=868.4,891.3
XS Rating Curve= 0 ,0
Exp/Cntr(USF)=0,0
Exp/Cntr=0.3,0.1

Type RM Length L Ch R = 1 ,216     ,,,
XS GIS Cut Line= 4
2466637.45272817586657.7000266792466372.95363504587538.851075311
2466778.92898729587963.279852663 2467921.5035582587821.803593545
#Sta/Elev= 30
       0 1679.39    26.3 1668.08    35.3 1659.87    54.5 1637.48    59.7 1634.29
   105.7 1633.82     122 1629.26   134.8 1628.62   293.6 1630.28   360.4 1623.33
   520.3 1623.67   590.1 1617.04   627.7 1620.01   744.6 1617.92   840.7 1619.86
   934.2 1618.08     992 1619.19    1006 1616.23  1026.7 1615.21  1071.2 1616.18
  1080.6 1617.86    1183 1620.24  1356.6 1618.54  1382.4 1618.64    1620 1617.22
  1906.9 1620.94    2551 1616.84  2591.4 1618.36  2615.3 1623.95  2658.6 1634.61
#Mann= 9 ,-1 , 0
       0     .06       0   134.8      .1       0    1006    .045       0
  1071.2      .1       0    1183     .06       0  1356.6     .05       0
  1382.4      .1       0    1620     .05       0  2615.3     .06       0
#XS Ineff= 2 , 0
          990.59 1621.39 1175.75         1621.57
Permanent Ineff=
       F       F
Bank Sta=1006,1071.2
XS Rating Curve= 0 ,0
Exp/Cntr(USF)=0,0
Exp/Cntr=0.3,0.1
LCMann Table=0

Chan Stop Cuts=-1
Use User Specified Reach Order=0
Composite Channel Slope=5